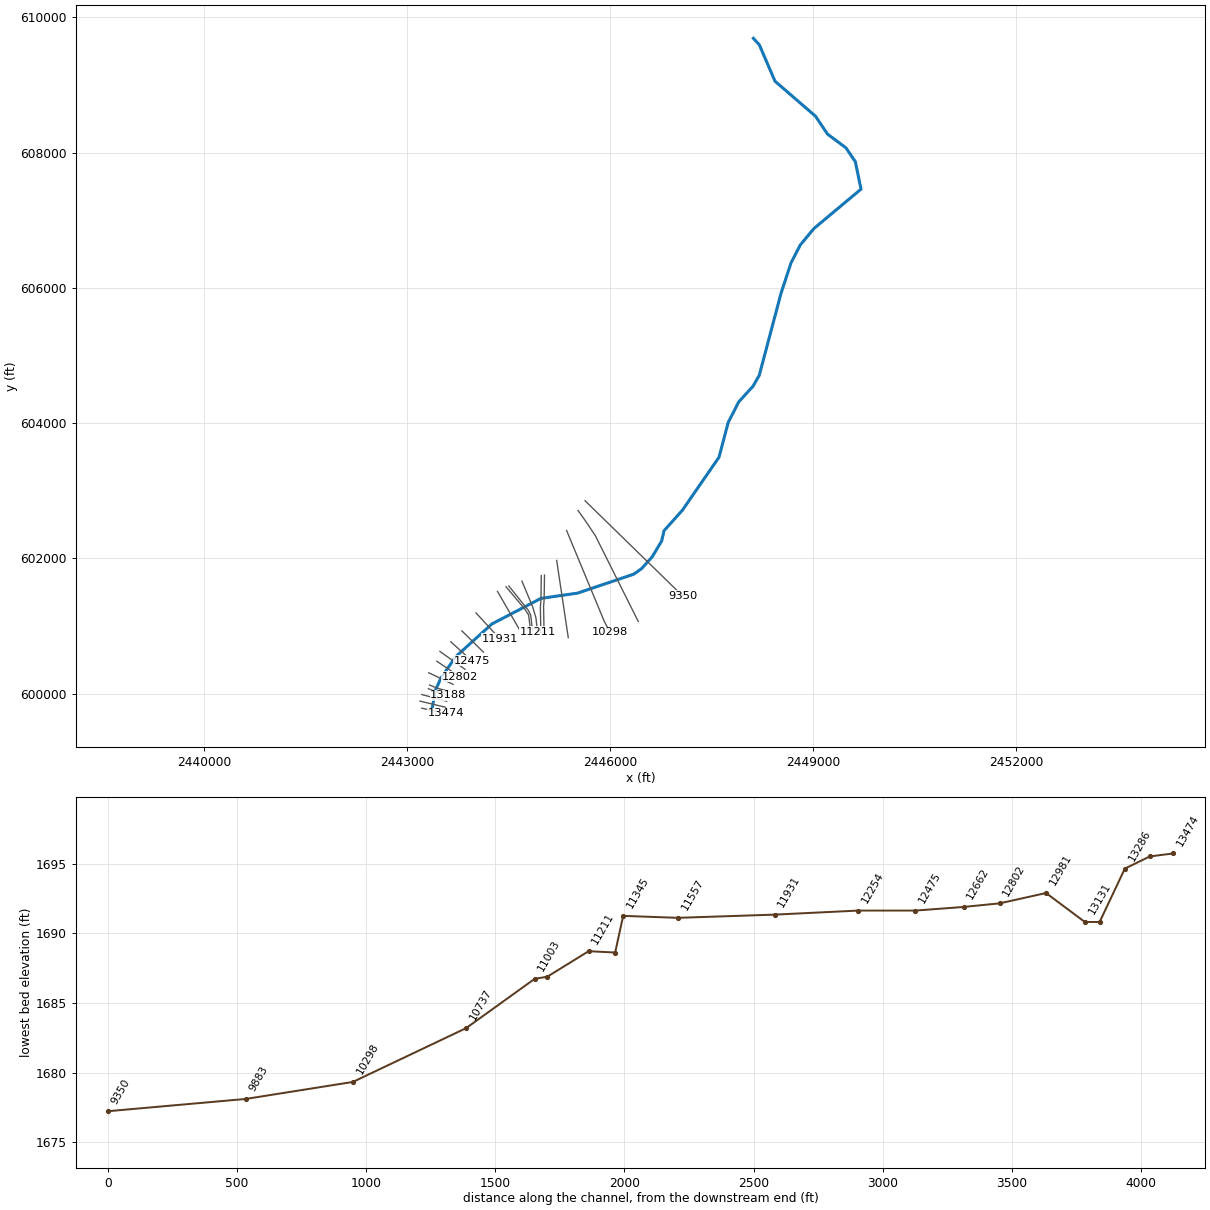
--- SBPOTOMC1.prj (project) ---

Proj Title=SBPOTOMC1
Current Plan=p01
Default Exp/Contr=0,0
English Units
Geom File=g01
Flow File=f01
Plan File=p01
BEGIN DESCRIPTION:
Stream Name: South Branch Potomac River
Flood Zone: Zone AE
Pendleton County, WV
WVDHSEM Flood Warning & Analysis Mapping
HEC-RAS Version: 5.0.7
Hydrology Method:
Regression with Gage Weighting
Model Notes: Applied known water surface elevation from South Branch Potomac River, Zone A
END DESCRIPTION:
DSS Export Rating Curves= 0
DSS Export Rating Curve Sorted= 0
DSS Export Volume Flow Curves= 0
DXF OffsetX= 0
DXF OffsetY= 0
DXF ScaleX= 0
DXF ScaleY= 0

--- SBPOTOMC1.p01 (plan) ---

Plan Title=Floodplain
Program Version=5.07
Short Identifier=Floodplain
Geom File=g01
Flow File=f01
Subcritical Flow
K Sum by GR= 0
Std Step Tol= 0.01
Critical Tol= 0.01
Num of Std Step Trials= 20
Max Error Tol= 0.3
Flow Tol Ratio= 0.001
Split Flow NTrial= 30
Split Flow Tol= 0.02
Split Flow Ratio= 0.02
Log Output Level= 0
Friction Slope Method= 1
Unsteady Friction Slope Method= 2
Unsteady Bridges Friction Slope Method= 1
Parabolic Critical Depth
Global Vel Dist= 0 , 0 , 0
Global Log Level= 0
CheckData=True
Encroach Param=-1 ,0,0, 0
Mapping Interval=1HOUR
Computation Time Step Use Courant=        0
Computation Time Step Use Time Series=    0
Computation Time Step Count To Double=0
Computation Time Step Max Doubling=0
Computation Time Step Max Halving=0
Computation Time Step Residence Courant=0
Run HTab= 0
Run UNet= 0
Run Sediment= 0
Run PostProcess= 0
Run WQNet= 0
Run RASMapper= 0
UNET Theta= 0
UNET Theta Warmup= 0
UNET ZTol= 0
UNET ZSATol= 0
UNET MxIter= 0
UNET Max Iter WO Improvement= 0
UNET MaxInSteps= 0
UNET DtIC= 0
UNET DtMin= 0
UNET MaxCRTS= 0
UNET WFStab= 0
UNET SFStab= 0
UNET WFX= 1
UNET SFX= 1
UNET 1D Methodology=Finite Difference
UNET DSS MLevel= 1
UNET Pardiso=0
UNET DZMax Abort= 0
UNET Use Existing IB Tables= 0
UNET Froude Reduction=False
UNET Froude Limit= 0
UNET Froude Power= 0
UNET D1 Cores= 0
UNET D2 Coriolis=0
UNET D2 Cores= 0
UNET D2 Theta= 1
UNET D2 Theta Warmup= 1
UNET D2 Z Tol= 0.01
UNET D2 Volume Tol= 0.01
UNET D2 Max Iterations= 20
UNET D2 Equation= 0
UNET D2 RampUpFraction=0.1
UNET D2 TimeSlices= 1
UNET D2 BCVolumeCheck=0
UNET D1D2 MaxIter= 0
UNET D1D2 ZTol=0.01
UNET D1D2 QTol=0.1
UNET D1D2 MinQTol=1
Write IC File= 0
Write IC File at Fixed DateTime=0
Write IC File at Sim End=0
Echo Input=False
Echo Parameters=False
Echo Output=False
Write Detailed= 0
HDF Write Warmup=0
HDF Write Time Slices=0
HDF Flush=0
HDF Face Node Velocities=0
HDF Compression= 1
HDF Chunk Size= 1
HDF Spatial Parts= 1
HDF Use Max Rows=0
HDF Fixed Rows= 1
Calibration Method= 0
Calibration Iterations= 20
Calibration Max Change=0.05
Calibration Tolerance=0.2
Calibration Maximum=1.5
Calibration Minimum=0.5
Calibration Optimization Method= 1
WQ AD Non Conservative
WQ ULTIMATE=-1
WQ Max Comp Step=1HOUR
WQ Output Interval=15MIN
WQ Output Selected Increments= 0
WQ Output face flow=0
WQ Output face velocity=0
WQ Output face area=0
WQ Output face dispersion=0
WQ Output cell volume=0
WQ Output cell surface area=0
WQ Output cell continuity=0
WQ Output cumulative cell continuity=0
WQ Output face conc=0
WQ Output face dconc_dx=0
WQ Output face courant=0
WQ Output face peclet=0
WQ Output face adv mass=0
WQ Output face disp mass=0
WQ Output cell mass=0
WQ Output cell source sink temp=0
WQ Output nsm pathways=0
WQ Output nsm derived pathways=0
WQ Output MaxMinRange=-1
WQ Daily Max Min Mean=-1
WQ Daily Range=0
WQ Daily Time=0
WQ Create Restart=0
WQ Fixed Restart=0
WQ System Summary=0
WQ Write To DSS=0
WQ Use Fixed Temperature=0
Sorting and Armoring Iterations= 10
XS Update Threshold= 0.02
Bed Roughness Predictor= 0
Hydraulics Update Threshold= 0.02
Energy Slope Method= 1
Volume Change Method= 1
Sediment Retention Method= 0
XS Weighting Method= 0
Number of US Weighted Cross Sections= 1
Number of DS Weighted Cross Sections= 1
Upstream XS Weight=0
Main XS Weight=1
Downstream XS Weight=0
Number of DS XS's Weighted with US Boundary= 1
Upstream Boundary Weight= 1
Weight of XSs Associated with US Boundary= 0
Number of US XS's Weighted with DS Boundary= 1
Downstream Boundary Weight= 0.5
Weight of XSs Associated with DS Boundary= 0.5
Percentile Method= 0
Sediment Output Level= 3
Mass or Volume Output= 0
Output Increment Type= 1
Profile and TS Output Increment= 1
XS Output Flag= 0
XS Output Increment= 10
Write Gradation File= 0
Read Gradation Hotstart= 0
Write HDF5 File= 1
Write Binary Output= 1
Write DSS Sediment File= 0
SV Curve= 0
Specific Gage Flag= 0

--- SBPOTOMC1.f01 (steady flow) ---

Flow Title=Flows
Program Version=5.07
Number of Profiles= 6
Profile Names=P100yr,P10yr,P25yr,P50yr,P500yr,P101yr
River Rch & RM=SBPOTOMC1,Main            ,13474
   30674   12316   18464   24120   51218   40300
River Rch & RM=SBPOTOMC1,Main            ,2835
   34373   13930   20821   27127   56896   44781
River Rch & RM=SBPOTOMC1,Main            ,0
   34933   14174   21178   27582   57757   45460
Boundary for River Rch & Prof#=SBPOTOMC1,Main            , 1
Up Type= 0
Dn Type= 1
Dn Known WS=1652.78
Boundary for River Rch & Prof#=SBPOTOMC1,Main            , 2
Up Type= 0
Dn Type= 1
Dn Known WS=1646.33
Boundary for River Rch & Prof#=SBPOTOMC1,Main            , 3
Up Type= 0
Dn Type= 1
Dn Known WS=1648.84
Boundary for River Rch & Prof#=SBPOTOMC1,Main            , 4
Up Type= 0
Dn Type= 1
Dn Known WS=1650.79
Boundary for River Rch & Prof#=SBPOTOMC1,Main            , 5
Up Type= 0
Dn Type= 1
Dn Known WS=1657.87
Boundary for River Rch & Prof#=SBPOTOMC1,Main            , 6
Up Type= 0
Dn Type= 1
Dn Known WS=1655.29
DSS Import GetInterval= 0
DSS Import GetPeak= 0
DSS Import FillOption= 0

--- SBPOTOMC1.g01 (geometry) ---

Geom Title=Geometry
Program Version=5.07

River Reach=SBPOTOMC1       ,Main
Reach XY= 30
2443359.72080189599751.2257560642443413.98250438600051.304224148
2443497.82584064600234.947885722 2443714.1528358600546.596540645
2444246.74724305 601028.276679652444971.97971646601406.726710141
2445513.25356831601484.901094481 2446344.2361583601765.229273975
2446462.23329763601849.5975435672446617.84814389602023.547983065
2446757.29668389602258.0019104782446791.76544698602408.297541648
2447060.37383364602707.7680713092447603.26119931603493.433166638
 2447740.3317913604009.9675666392447896.01783164604314.128375649
 2448104.9983848604543.1932062212448197.90666355604703.111849651
2448521.14551839605921.4365127242448668.01464722606368.685290143
2448804.80505605606633.4790518882449007.03332613 606877.62652947
2449702.94991331607459.5968222322449618.26832414607866.220680892
 2449480.4306733608070.1628583072449207.50733463608273.681808233
2449030.17304364608538.1674997212448431.54333539609055.863642812
2448199.76131864609594.2431434842448111.99935505609689.944723725

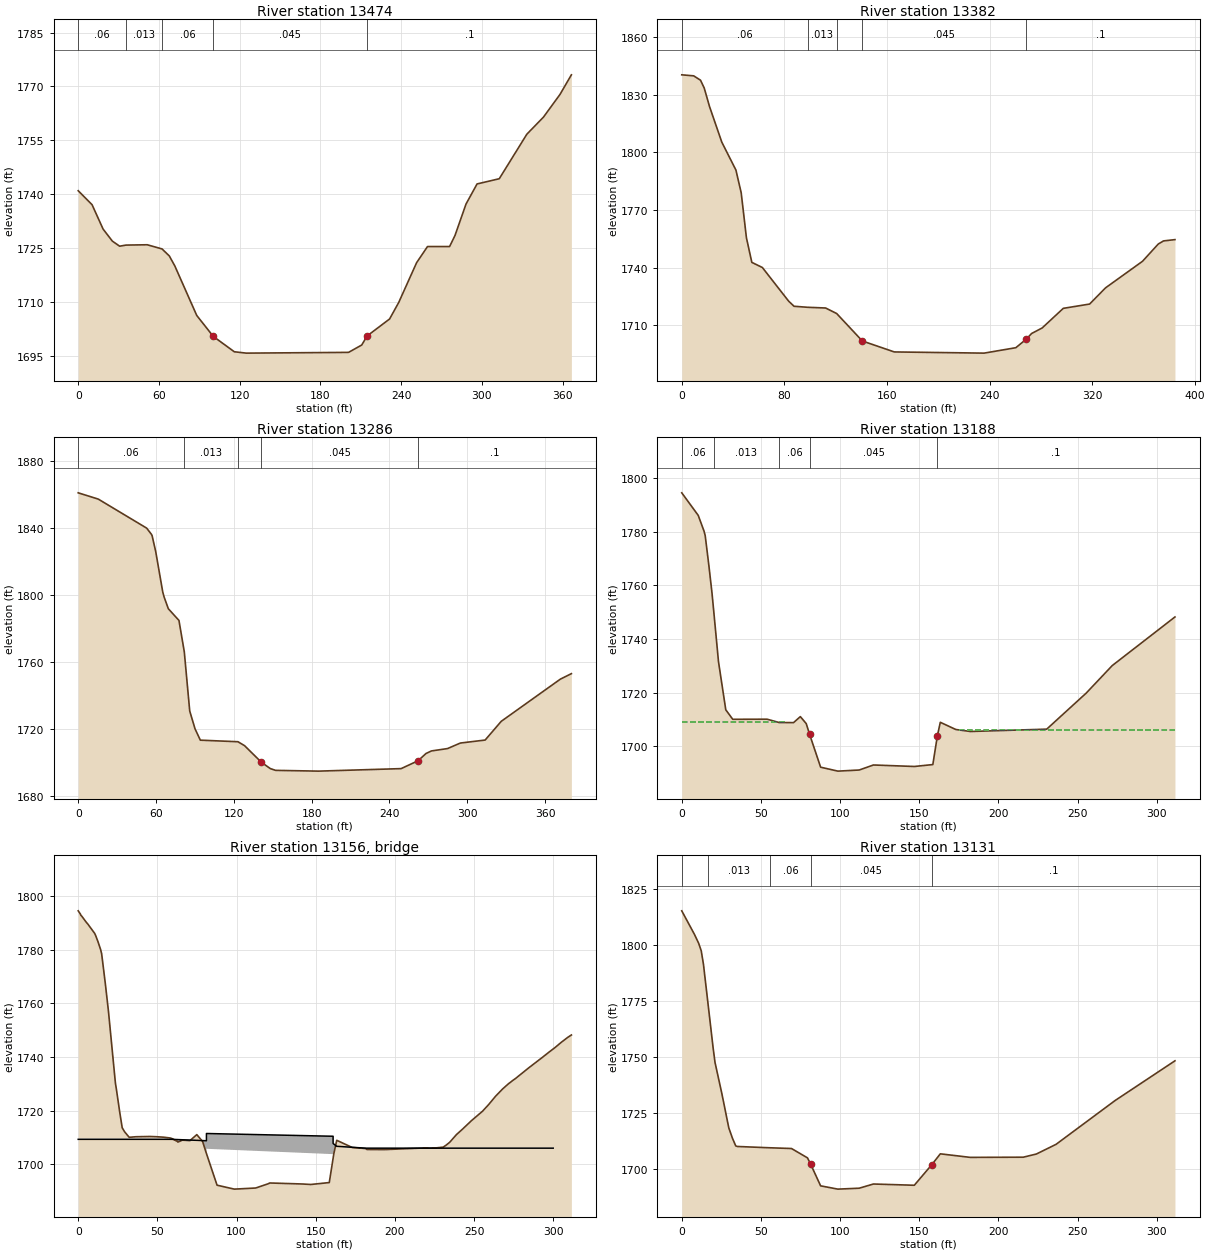
Type RM Length L Ch R = 1 ,13474   ,94.1,91.9,88.8
XS GIS Cut Line= 4
2443212.71617463599783.2128968092443313.76288855599760.641091555
2443486.62704414599725.5604530572443571.12195389599706.491265476
#Sta/Elev= 30
       0 1740.96    10.3 1737.07    18.5 1730.28    25.4 1726.92    30.8 1725.51
    35.5 1725.82    51.3 1725.91    62.3 1724.75    67.7  1722.8    71.8 1720.02
    88.1 1706.22   100.4 1700.38     116 1696.11   124.9 1695.73   200.9 1695.94
   210.7 1697.99   214.7 1700.51   231.4 1705.24   238.2 1709.85   251.5 1720.93
   259.6 1725.42     276 1725.42     280 1728.49   288.2 1737.25   296.4 1742.85
   312.9  1744.3   333.4  1756.7   345.7 1761.44     358 1767.76   366.5 1773.24
#Mann= 5 ,-1 , 0
       0     .06       0    35.5    .013       0    62.3     .06       0
   100.4    .045       0   214.7      .1       0
Bank Sta=100.4,214.7
XS Rating Curve= 0 ,0
Exp/Cntr=0.3,0.1

Type RM Length L Ch R = 1 ,13382   ,98.3,96.1,93.3
XS GIS Cut Line= 2
 2443185.7050738599887.480732888 2443559.4031453599797.637080565
#Sta/Elev= 30
       0 1840.25     9.3 1839.72    14.6 1837.46    17.5 1833.39    21.6 1823.83
    31.2 1805.24    42.2 1790.73    46.3 1778.95    50.4 1755.46    54.6 1742.71
    62.8 1740.04    83.3 1722.53    87.5 1719.88    98.1 1719.35   112.1 1718.98
   120.7 1716.11  140.711701.825   165.6 1696.13   235.6 1695.51   260.3 1698.33
   268.5 1702.79   272.6 1705.72   280.8 1708.58   297.3  1718.8   317.8 1721.03
   330.2 1729.45     359 1743.26   371.3 1752.25   375.4 1753.87   384.3 1754.54
#Mann= 5 ,-1 , 0
       0     .06       0    98.1    .013       0   120.7     .06       0
  140.71    .045       0   268.5      .1       0
Bank Sta=140.71,268.5
XS Rating Curve= 0 ,0
Exp/Cntr=0.3,0.1

Type RM Length L Ch R = 1 ,13286   ,102,97.7,93.4
XS GIS Cut Line= 2
2443211.74668838599985.1370336412443578.93427423599886.178570136
#Sta/Elev= 30
       0  1861.2    15.5 1857.44    52.8 1840.07    56.5 1836.33      57 1835.54
    59.8 1825.93    65.2 1801.83    66.3 1798.73    69.5 1791.84    77.7 1784.82
    81.8 1766.12      86 1730.61    90.1 1719.93    94.2 1713.17   123.2 1712.23
   128.3 1709.87   141.3 1699.92   148.1 1696.18   152.2  1695.1   185.4 1694.64
     249 1696.14   262.1 1700.85   268.2  1705.2   272.4 1706.72   284.8 1708.14
   294.7 1711.45   313.8 1713.24   326.2 1724.44   371.8 1749.69   380.3 1752.98
#Mann= 5 ,-1 , 0
       0     .06       0    81.8    .013       0   123.2     .06       0
   141.3    .045       0   262.1      .1       0
Bank Sta=141.3,262.1
XS Rating Curve= 0 ,0
Exp/Cntr=0.5,0.3

Type RM Length L Ch R = 1 ,13188   ,56.6,57.2,56.7
BEGIN DESCRIPTION:
Incorporated Survey Data from XS 54071SPR032BU
END DESCRIPTION:
XS GIS Cut Line= 6
2443309.13756973600071.7749837342443364.22144905600048.348521397
 2443420.9624773600028.7609621442443461.67433813600013.640585557
2443479.55619213600009.6189400552443604.97096756 599975.94151397
#Sta/Elev= 30
       0 1794.49    10.4 1786.09    14.1 1780.17    14.8 1778.57    17.1 1767.54
    19.1 1757.15    20.2 1750.38    23.2 1731.59    27.8 1713.67    32.2 1710.12
    53.9 1710.16    61.5 1708.92    70.61708.885    74.91711.119    78.61708.526
   80.72 1704.57    87.71692.281    98.61690.813  112.071691.225  121.061693.101
  146.871692.543  158.581693.256  161.45 1703.97   163.31709.003   173.11706.318
   182.3 1705.58   230.5 1706.45   255.4 1719.85   271.9 1730.14   311.5 1748.24
#Mann= 5 ,-1 , 0
       0     .06       0    20.2    .013       0    61.5     .06       0
   80.72    .045       0  161.45      .1       0
#XS Ineff= 2 , 0
              65 1709.21     175         1706.32
Permanent Ineff=
       F       F
Bank Sta=80.72,161.45
XS Rating Curve= 0 ,0
Exp/Cntr=0.5,0.3

Type RM Length L Ch R = 3 ,13156   ,,,
BEGIN DESCRIPTION:
Props Gap Rd
Incorporated survey data from 54071SPR030RP.
Assumed deck thickness of 3 based on low chord data and included railing. The bridge survey report states a railing height of 2.7 ft.
END DESCRIPTION:
Bridge Culvert--1,0,-1,-1, 0
Deck Dist Width WeirC Skew NumUp NumDn MinLoCord MaxHiCord MaxSubmerge Is_Ogee
15,25,2.6,0, 9, 9, , , 0.98, 0, 0,0,,
       0      59      81      81     161     161   163.3   181.6     300
1709.3671709.367 1708.84 1711.541710.5131707.813 1706.771706.0721706.072
                         1705.84 1703.85
       0      59      80      80     160     160   163.3   181.6     300
1709.3671709.367 1708.84 1711.541710.5131707.813 1706.771706.0721706.072
                         1705.84 1703.85
Pier Skew, UpSta & Num, DnSta & Num=  ,520, 2 ,480, 2 , 0 , 0 , 0 ,,
       3       3
       0    1708
       3       3
       0    1708
BR Coef=-1 , 1 , 0 ,, 0 ,,,0.8,0,1.2,0,
WSPro=,,,, 1 ,,,, 0 ,,,, 0 ,,,,-1 ,-1 ,-1 , 0 , 0 , 0 , 0 , 0
BR U #Sta/Elev= 128
       0 1794.49     1.4 1793.27     1.7 1792.85     2.3 1792.47     4.9 1790.38
     6.1 1789.55       8 1788.05    10.4 1786.09      11 1785.32    12.5    1783
    14.1 1780.17    14.8 1778.57    16.5 1770.45    17.1 1767.54    19.1 1757.15
    20.2 1750.38    22.7 1734.75    23.2 1731.59    23.5 1730.34    24.1 1728.12
    26.3 1719.22    27.8 1713.67    29.3 1712.18    31.6 1710.58    32.2 1710.12
    35.4 1710.29    36.5 1710.33    40.9 1710.39    45.2 1710.42    49.6 1710.33
   53.13 1710.19    53.9 1710.16    56.8 1709.98    58.3 1709.85    59.9 1709.47
    61.5 1708.92    62.5 1708.65      63 1708.34    65.8 1709.06    70.61708.885
    74.91711.119    78.61708.526   80.72 1704.57    87.71692.281    98.61690.813
  112.071691.225   119.81692.766  121.061693.101  141.87 1692.72  146.871692.543
  158.581693.256  161.45 1703.97   163.31709.003   173.11706.318   181.61705.936
   182.3 1705.58   183.2 1705.58   184.9 1705.62   189.1 1705.55   189.7 1705.55
   192.2 1705.53   193.2 1705.54   193.6 1705.54   196.3 1705.61   197.4 1705.61
   201.5 1705.76   207.6 1705.92   209.3 1705.97   210.6 1706.01   218.1 1706.19
   219.1 1706.17   221.9 1706.12   222.2 1706.12   222.4 1706.12   226.4  1706.2
   227.6 1706.28   228.9 1706.35   230.5 1706.45   232.2 1707.11   233.3 1707.63
   234.6 1708.24   235.4 1708.78   238.9 1711.12     242 1712.74   242.9 1713.25
   244.6 1714.21   245.2 1714.59   247.1 1715.66   248.5 1716.38   250.2 1717.23
   251.2 1717.72   251.8 1718.01   255.4 1719.85   258.3 1721.69   259.5 1722.49
   261.6 1723.97   263.6 1725.41   267.8 1727.98   268.1 1728.15   269.3 1728.78
   271.4 1729.86   271.9 1730.14   272.9 1730.57   274.6 1731.36   276.1 1731.97
   277.9 1732.82   278.6 1733.13   280.2 1733.91   284.4 1735.93   284.7 1736.06
   288.5 1737.77   289.9 1738.39     291 1738.89   292.6 1739.63   295.5 1741.01
   296.8 1741.59   297.5 1741.91   300.1 1743.07   300.7 1743.35   300.9 1743.43
   301.2 1743.57     304 1744.99   305.1  1745.5   306.9 1746.31   307.3 1746.49
   309.2 1747.35   310.5 1747.87   311.5 1748.24
BR U #Mann= 5
       0     .06    20.2    .013    61.5     .06   80.72     .04  161.45      .1
BR D #Sta/Elev= 124
       0 1815.35     1.5 1813.36     4.6  1809.2     6.8 1806.29       8 1804.83
     8.9 1803.37    10.7 1800.77    12.3 1797.47    13.7 1791.43    16.4 1774.91
    16.7 1773.58      17 1771.29    19.8 1754.05      21 1747.52    22.9 1741.31
      24 1737.78    25.4 1733.31    25.9  1731.3    27.2  1726.7      29 1720.72
    29.7 1718.24    31.5 1714.63      32 1713.62    34.1 1710.15    35.1  1709.9
    37.4  1709.7    38.1 1709.67    42.7 1709.67    46.7 1709.63    51.4  1709.5
   54.611709.361    55.8 1709.31    59.9 1709.05    64.3 1708.86    68.6 1708.81
    69.31708.987    79.41704.808   81.42 1701.96    87.71692.281    98.61690.813
  112.071691.225   119.81692.766  121.061693.101  141.87 1692.72  146.871692.543
  157.88 1701.71  163.311706.609   167.71706.353  171.411705.998   178.5 1705.07
   182.2 1705.02   182.8 1705.02   186.1 1705.09   190.9 1705.11   192.6 1705.12
     195 1705.14   195.9 1705.15     199 1705.16   199.1 1705.16   202.4 1705.18
   203.3 1705.19   207.4 1705.13   211.6 1705.01   212.2 1705.02   215.5  1705.1
   215.7  1705.1   216.2 1705.15   218.7 1705.37   219.9 1705.48   221.9    1706
     222 1706.02     224 1706.53   225.2 1706.97   227.5 1707.77   228.2 1707.99
   231.8 1709.01   232.3 1709.17   233.2 1709.54     235 1710.26   236.4 1710.85
   240.6  1712.9   245.3 1715.57   248.1  1717.2   248.9  1717.6   250.2 1718.25
   251.4 1718.85     253 1719.64   254.6 1720.48   255.9 1721.12   257.1  1721.8
   257.9 1722.17   261.3 1723.97   261.5 1724.08   264.4  1725.5   267.2 1726.97
     271 1729.04   272.8 1729.99   273.7 1730.46   274.2  1730.7   276.1 1731.55
   277.9 1732.33   278.5 1732.62   280.8 1733.57     282 1734.14     284 1735.18
   284.2 1735.25   287.3 1736.85   289.8 1738.13   290.3 1738.36   290.5 1738.49
   293.8 1740.01   294.4  1740.3   295.5 1740.79   297.1 1741.54   298.6 1742.21
   300.3 1743.05   301.1 1743.42   302.7 1744.15   303.6 1744.58   306.8 1746.13
   306.9 1746.16     307  1746.2   310.1 1747.63   311.5 1748.23
BR D #Mann= 5
       0     .06    16.4    .013    55.8     .06   81.42     .04  157.88      .1
BC Design=,, 0 ,, 0 ,,,,,,
BC Use User HTab Curves=0
BC User HTab FreeFlow(D)= 0

Type RM Length L Ch R = 1 ,13131   ,156.2,150.2,136
BEGIN DESCRIPTION:
Incorporated Survey Data from XS 54071SPR028BD for the banks and 54071SPR032BU for the channel
END DESCRIPTION:
XS GIS Cut Line= 6
2443327.40557781600125.5455454742443382.48945713600102.119083136
2443439.23048539600082.5315238982443479.94234622600067.411147311
2443497.82420023 600063.389501812443623.23897564600029.712075725
#Sta/Elev= 30
       0 1815.35       8 1804.83    10.7 1800.77    12.3 1797.47    13.7 1791.43
    16.4 1774.91    19.8 1754.05      21 1747.52    25.4 1733.31    29.7 1718.24
      32 1713.62    34.1 1710.15    35.1  1709.9    55.8 1709.31    69.31708.987
    79.41704.808   81.42 1701.96    87.71692.281    98.61690.813  112.071691.225
  121.061693.101  146.871692.543  157.88 1701.71  163.311706.609   182.2 1705.02
   215.7  1705.1     224 1706.53   236.4 1710.85   273.7 1730.46   311.5 1748.23
#Mann= 5 ,-1 , 0
       0     .06       0    16.4    .013       0    55.8     .06       0
   81.42    .045       0  157.88      .1       0
#XS Ineff= 2 , 0
              75  1705.6     165          1705.4
Permanent Ineff=
       F       F
Bank Sta=81.42,157.88
XS Rating Curve= 0 ,0
Exp/Cntr=0.5,0.3

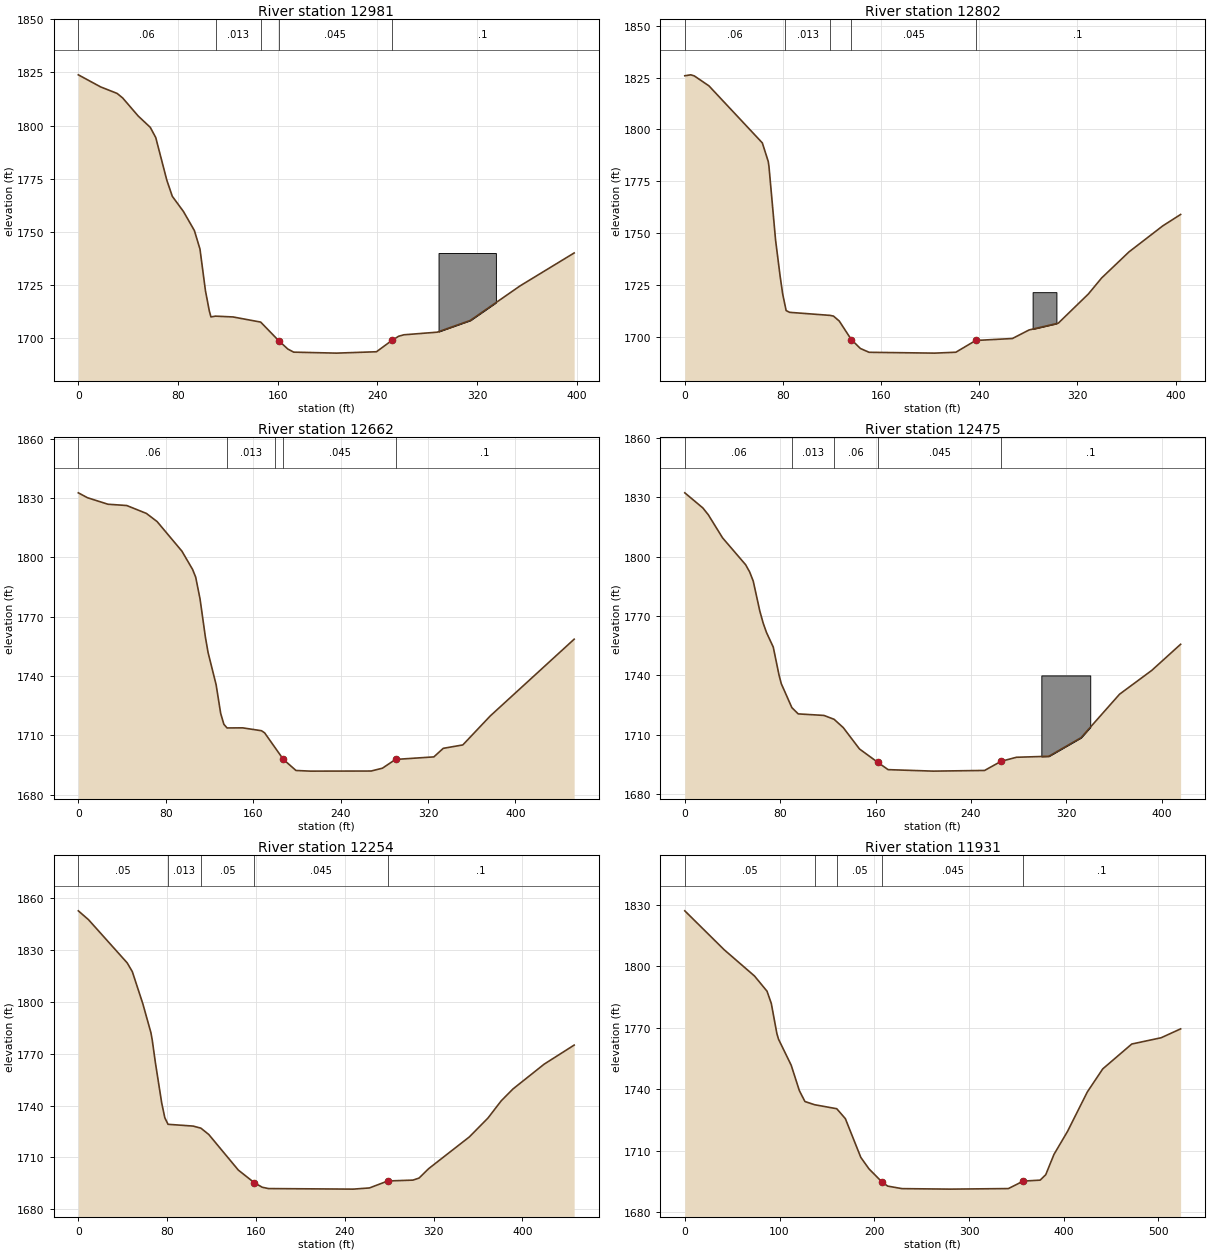
Type RM Length L Ch R = 1 ,12981   ,187.9,178.9,164.9
XS GIS Cut Line= 2
2443314.61131205600306.7515478882443673.98624948600136.178726316
#Sta/Elev= 30
       0  1823.9    17.9 1818.21    31.1 1815.15    35.6    1813      48 1804.53
    57.7 1799.19    62.1 1794.39      71  1774.3    75.4 1766.71    84.3  1759.6
    93.1 1750.61    97.6 1741.87     102 1722.22   105.1 1712.73   106.4 1709.94
   110.1  1710.3   124.1 1709.92   146.3  1707.5   160.7 1698.79   168.1  1694.8
   172.8 1693.35   207.2 1692.89   239.2 1693.54  251.511698.844     257 1700.84
   261.2 1701.52   287.9 1702.75   314.5 1708.28   354.5 1724.58   397.8 1740.04
#Mann= 5 ,-1 , 0
       0     .06       0   110.1    .013       0   146.3     .06       0
   160.7    .045       0  251.51      .1       0
#Block Obstruct= 1 ,-1
     289     335    1740
Bank Sta=160.7,251.51
XS Rating Curve= 0 ,0
Exp/Cntr=0.3,0.1

Type RM Length L Ch R = 1 ,12802   ,141.3,139.8,137.7
XS GIS Cut Line= 2
2443434.40306722600477.3243694752443769.03855281600250.761830479
#Sta/Elev= 30
       0 1825.84     4.9 1826.29     7.8 1825.75    19.7 1820.96    63.2 1793.47
      68 1784.54    68.6 1782.13      74 1746.55    77.7 1729.22    79.8 1720.59
    81.9 1714.64    82.6 1712.65    85.5 1711.81   118.5 1710.34   121.2 1709.99
   125.9 1707.61   135.7 1698.69   143.1 1694.39   150.2 1692.55   203.6 1692.15
   220.9 1692.58   237.1 1698.25     267 1699.19   280.6 1703.32   304.4 1706.59
   328.9 1720.65   339.7 1728.36     362 1740.93   389.6 1753.51   404.1 1758.98
#Mann= 5 ,-1 , 0
       0     .06       0    81.9    .013       0   118.5     .06       0
   135.7    .045       0   237.1      .1       0
#Block Obstruct= 1 ,-1
  283.47  302.871721.528
Bank Sta=135.7,237.1
XS Rating Curve= 0 ,0
Exp/Cntr=0.3,0.1

Type RM Length L Ch R = 1 ,12662   ,193.1,187.3,175.3
XS GIS Cut Line= 2
2443479.97581072600621.8559045642443849.76772206600358.834777057
#Sta/Elev= 30
       0 1832.66     8.3  1830.2    27.1 1826.89    44.3 1826.24    62.3 1822.24
    72.1 1818.12    94.8 1803.16   104.5 1793.99   107.4 1790.04   111.4 1778.97
   116.3 1759.64   118.8 1751.75   126.1 1735.62   130.3 1721.05   133.2 1715.59
   136.1 1713.73   150.4 1713.78   167.6 1712.33   170.5 1711.26   187.7 1697.79
   199.2 1692.22   212.2 1691.89     268 1691.94   278.3 1693.37  290.311697.806
   325.4 1699.09     334 1703.42   351.9 1705.14     377  1719.8   453.8 1758.62
#Mann= 5 ,-1 , 0
       0     .06       0   136.1    .013       0   180.3     .05       0
   187.7    .045       0  290.31      .1       0
Bank Sta=187.7,290.31
XS Rating Curve= 0 ,0
Exp/Cntr=0.3,0.1

Type RM Length L Ch R = 1 ,12475   ,223.6,220.9,216.4
XS GIS Cut Line= 2
2443640.13231455600765.0849488082443948.72585747600486.439180642
#Sta/Elev= 30
       0 1832.29    15.2 1824.62    19.7 1821.21    31.7 1809.51      51 1795.96
    54.4  1792.3    57.4 1787.66    62.9 1772.56    65.7  1766.5    68.5 1761.71
    74.2  1754.3      79 1740.24    80.9 1735.84    89.8 1723.72    95.1 1720.56
   116.7 1719.78   125.2 1717.82   132.9 1713.62   146.5 1702.83     162 1696.01
   170.5 1692.38   208.3 1691.63   251.4 1691.97  265.15 1696.56   278.1 1698.63
   305.3 1699.14   332.3 1708.52   364.6 1730.51   391.6 1742.54   415.8 1755.75
#Mann= 5 ,-1 , 0
       0     .06       0    89.8    .013       0   125.2     .06       0
     162    .045       0  265.15      .1       0
#Block Obstruct= 1 ,-1
     299     340    1740
Bank Sta=162,265.15
XS Rating Curve= 0 ,0
Exp/Cntr=0.3,0.1

Type RM Length L Ch R = 1 ,12254   ,326.1,323.1,319.2
XS GIS Cut Line= 2
2443804.19465047600926.5432873072444121.90300456600612.741093397
#Sta/Elev= 30
       0 1852.71     9.2 1847.56      44 1822.59    48.6 1817.56    58.1 1798.93
    65.4 1782.13    66.6 1777.82    69.4 1764.87    75.1 1741.49    77.9 1732.95
    80.8 1729.15   103.4 1728.12   110.4 1726.92   117.5 1723.25   144.1 1702.66
  158.481695.353   165.6 1692.73   171.3 1691.95   247.6 1691.63   262.2 1692.31
   278.7 1696.34   301.4 1696.85   306.9 1698.02   315.5 1703.46   352.2 1721.85
     369  1732.8   380.9 1742.74   391.5 1749.61   419.6 1763.97   446.6    1775
#Mann= 5 ,-1 , 0
       0     .05       0    80.8    .013       0   110.4     .05       0
  158.48    .045       0   278.7      .1       0
Bank Sta=158.48,278.7
XS Rating Curve= 0 ,0
Exp/Cntr=0.3,0.1

Type RM Length L Ch R = 1 ,11931   ,392.4,374.6,351.7
XS GIS Cut Line= 2
2444012.96194947601191.7343579832444367.12889205600806.317477897
#Sta/Elev= 30
       0 1826.95    41.5 1808.02    73.6 1795.19    86.8 1787.78    91.3 1781.85
    97.2 1767.15    98.9 1764.44   112.3 1751.74   120.9 1739.38   126.8 1734.03
     137 1732.47   160.4 1730.52   169.5 1725.68   185.8 1706.81   194.4 1701.23
   208.5 1694.66   214.2 1692.81   229.3 1691.58   280.5 1691.34   341.6 1691.61
   357.3 1695.25   375.1 1695.72     381 1698.36   389.7 1708.25   403.9 1719.38
   424.9 1738.68   441.2 1749.93   471.8 1762.04   502.9 1765.11   523.4 1769.43
#Mann= 5 ,-1 , 0
       0     .05       0     137    .013       0   160.4     .05       0
   208.5    .045       0   357.3      .1       0
Bank Sta=208.5,357.3
XS Rating Curve= 0 ,0
Exp/Cntr=0.3,0.1

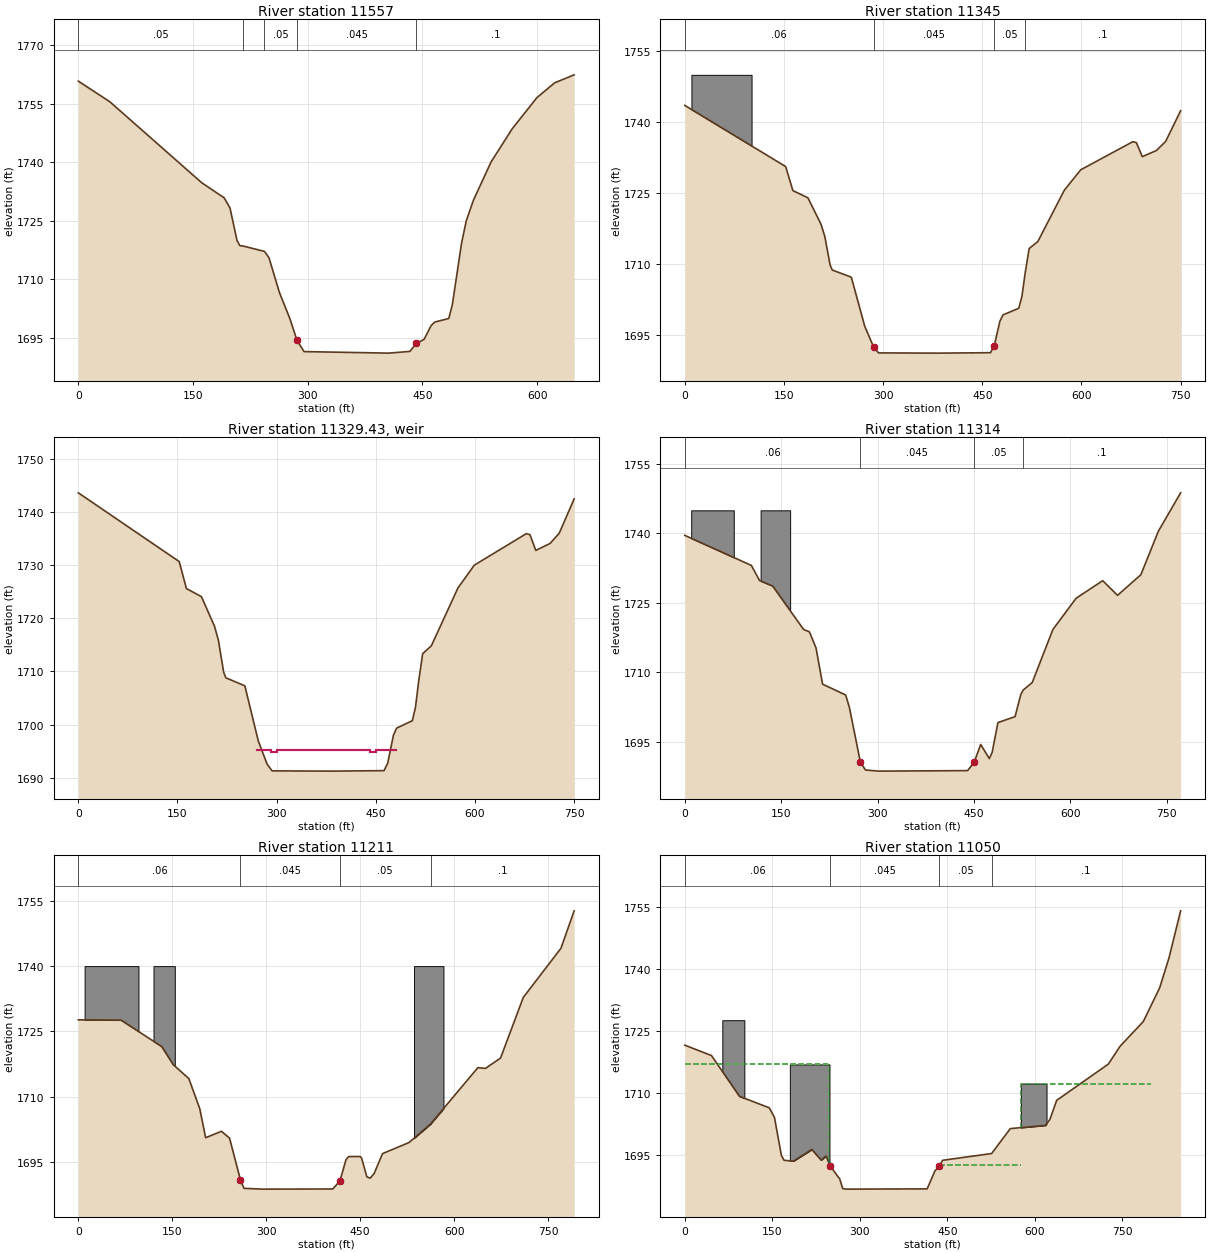
Type RM Length L Ch R = 1 ,11557   ,191.5,211.9,223.3
XS GIS Cut Line= 2
 2444330.2362493601510.7445467262444653.58698055600948.678741723
#Sta/Elev= 30
       0 1760.77    41.1 1755.51   161.3 1734.76   190.7 1730.89   198.3 1728.31
   207.5 1719.99   211.2 1718.65   215.5 1718.54   243.4 1717.17   249.3 1715.56
   262.9 1706.69   276.7 1699.92   285.9  1694.4   295.2  1691.5   405.9 1691.11
   433.6 1691.55   442.2 1693.63   452.1 1694.62   461.3 1698.14   465.9 1699.05
   484.4 1699.98     489 1703.39   501.2 1719.33   507.4 1725.07   516.7 1730.28
   539.7 1740.06   567.4 1748.57   599.7 1756.55   622.8 1760.33   648.4 1762.39
#Mann= 5 ,-1 , 0
       0     .05       0   215.5    .013       0   243.4     .05       0
   285.9    .045       0   442.2      .1       0
Bank Sta=285.9,442.2
XS Rating Curve= 0 ,0
Exp/Cntr=0.5,0.3

Type RM Length L Ch R = 1 ,11345   ,33.3,31.1,32.1
XS GIS Cut Line= 4
  2444456.436937601579.0181443262444732.27730559601251.647157422
2444789.87034959601162.7315807322444817.15126516600948.525873251
#Sta/Elev= 30
       0 1743.55   152.6 1730.63   163.5 1725.56   186.2 1724.04   206.1 1718.44
   211.8 1715.87   219.9  1709.8   223.1 1708.79   251.9 1707.28   272.2 1696.92
   285.6 1692.55   293.1  1691.3     382 1691.25   462.4 1691.34     468 1692.76
   476.6 1697.97   481.4 1699.33   505.2 1700.72     510 1703.26   514.8 1708.13
   520.9 1713.33     534  1714.8   574.2 1725.67     599 1729.96   677.7 1735.88
   683.1 1735.69     692 1732.73   713.5 1734.03   727.4 1735.95     750 1742.42
#Mann= 4 ,-1 , 0
       0     .06       0   285.6    .045       0     468     .05       0
   514.8      .1       0
#Block Obstruct= 1 ,-1
      10     101    1750
Bank Sta=285.6,468
XS Rating Curve= 0 ,0
Exp/Cntr(USF)=0,0
Exp/Cntr=0.5,0.3

Type RM Length L Ch R = 5 ,11329.43,,,
BEGIN DESCRIPTION:
Weir elevation based on LiDAR. Weir hieght is defined as 4 ft
END DESCRIPTION:
IW Pilot Flow=0
#Inline Weir SE= 10
     270 1695.31     291 1695.31     291 1694.81     301 1694.81     301 1695.31
     441 1695.31     441 1694.81     451 1694.81     451 1695.31     480 1695.31
IW Dist,WD,Coef,Skew,MaxSub,Min_El,Is_Ogee,SpillHt,DesHd
11,7,2.6,0,0.98,, 0 ,,,0,0,
Inline Weir Flap Gates= 0
IW Outlet Rating Curve= 0 ,False,,

Type RM Length L Ch R = 1 ,11314   ,135.1,102.4,72.9
XS GIS Cut Line= 4
 2444497.8635125601590.1325914122444785.82873246 601231.43907181
2444821.19288228 601159.700367892444847.46339358 600929.32819192
#Sta/Elev= 30
       0 1739.58   103.6 1733.09   116.4 1729.82   136.7 1728.64     185 1719.23
     194 1718.73   204.2 1715.29   214.5 1707.42   250.4 1705.08   256.2  1702.4
   273.2 1690.64   281.2 1688.86   301.7 1688.62   440.2 1688.73   450.4 1690.51
   460.6 1694.38     474 1691.33   478.4 1692.66   487.4 1699.11   514.1  1700.4
     523 1705.18   526.8 1706.15   540.8 1707.77     573 1719.24   609.2    1726
   650.5 1729.79   673.6 1726.62   709.9 1731.07   737.2 1740.49   771.8 1748.78
#Mann= 4 ,-1 , 0
       0     .06       0   273.2    .045       0   450.4     .05       0
   526.8      .1       0
#Block Obstruct= 2 ,-1
      10   76.22    1745     118     164    1745
Bank Sta=273.2,450.4
XS Rating Curve= 0 ,0
Exp/Cntr(USF)=0,0
Exp/Cntr=0.5,0.3

Type RM Length L Ch R = 1 ,11211   ,207.1,160.8,104.4
XS GIS Cut Line= 4
2444691.86113437601661.8712953332444850.49460642601280.948881558
2444898.99401189601117.2633881062444921.22290606600910.130510589
#Sta/Elev= 30
       0 1727.65    68.2 1727.59   133.2  1721.5   151.3 1717.38   176.5 1714.13
   193.9 1707.22   203.3 1700.54   228.5 1702.02   241.5 1700.44   258.9 1690.81
   264.5  1688.9   293.5 1688.72   406.2 1688.75   417.7 1690.58   427.3 1695.46
   431.5  1696.2   449.9 1696.23   452.3 1695.87   460.7 1691.56     466 1691.23
   472.4 1692.33   485.7 1696.88     528 1699.43   562.5 1703.71     638 1716.66
   650.1 1716.48   674.2 1718.87   710.5 1732.81   770.6  1744.1   791.7 1752.72
#Mann= 4 ,-1 , 0
       0     .06       0   258.9    .045       0   417.7     .05       0
   562.5      .1       0
#Block Obstruct= 3 ,-1
      10      96    1740     120     154    1740     536     583    1740
Bank Sta=258.9,417.7
XS Rating Curve= 0 ,0
Exp/Cntr(USF)=0,0
Exp/Cntr=0.5,0.3

Type RM Length L Ch R = 1 ,11050   ,49.5,47.8,48.6
BEGIN DESCRIPTION:
Incorporated survey data from 54071SPR022CU
END DESCRIPTION:
XS GIS Cut Line= 6
2444977.62143748601744.5888953062444974.22774348601493.973254815
2444971.86980855 601385.820255892444967.60144439601318.584497973
2444963.85735738601286.963170141 2444971.2585893600894.938363642
#Sta/Elev= 30
       0 1721.58    45.7 1719.08    93.7 1709.25   144.8 1706.48   153.7 1704.19
   165.7 1694.96   170.3 1693.82   186.1 1693.63   217.8 1696.44   233.7 1693.88
   242.1 1694.87   249.2  1692.5   265.7 1689.31  270.83    1687  277.38 1686.88
  415.53 1686.94  428.86 1691.28  436.32 1692.39     442 1693.83   526.1 1695.46
   558.1 1701.47   618.3 1702.24   625.9 1703.64   637.6 1708.28   726.2 1717.02
   746.2  1721.3   786.2 1727.29   814.2 1735.41   830.2 1742.64   850.1 1753.96
#Mann= 4 ,-1 , 0
       0     .06       0   249.2    .045       0  436.32     .05       0
   526.1      .1       0
#XS Ineff= 4 ,-1
       0  248.05 1716.94  248.05   248.5 1693.42     437  576.21 1692.61
  576.21     800 1712.33
Permanent Ineff=
       F       F       F       F
#Block Obstruct= 3 ,-1
   64.34   102.11727.596  180.06  248.051716.936  576.21   620.21712.326
Bank Sta=249.2,436.32
XS Rating Curve= 0 ,0
Exp/Cntr=0.5,0.3

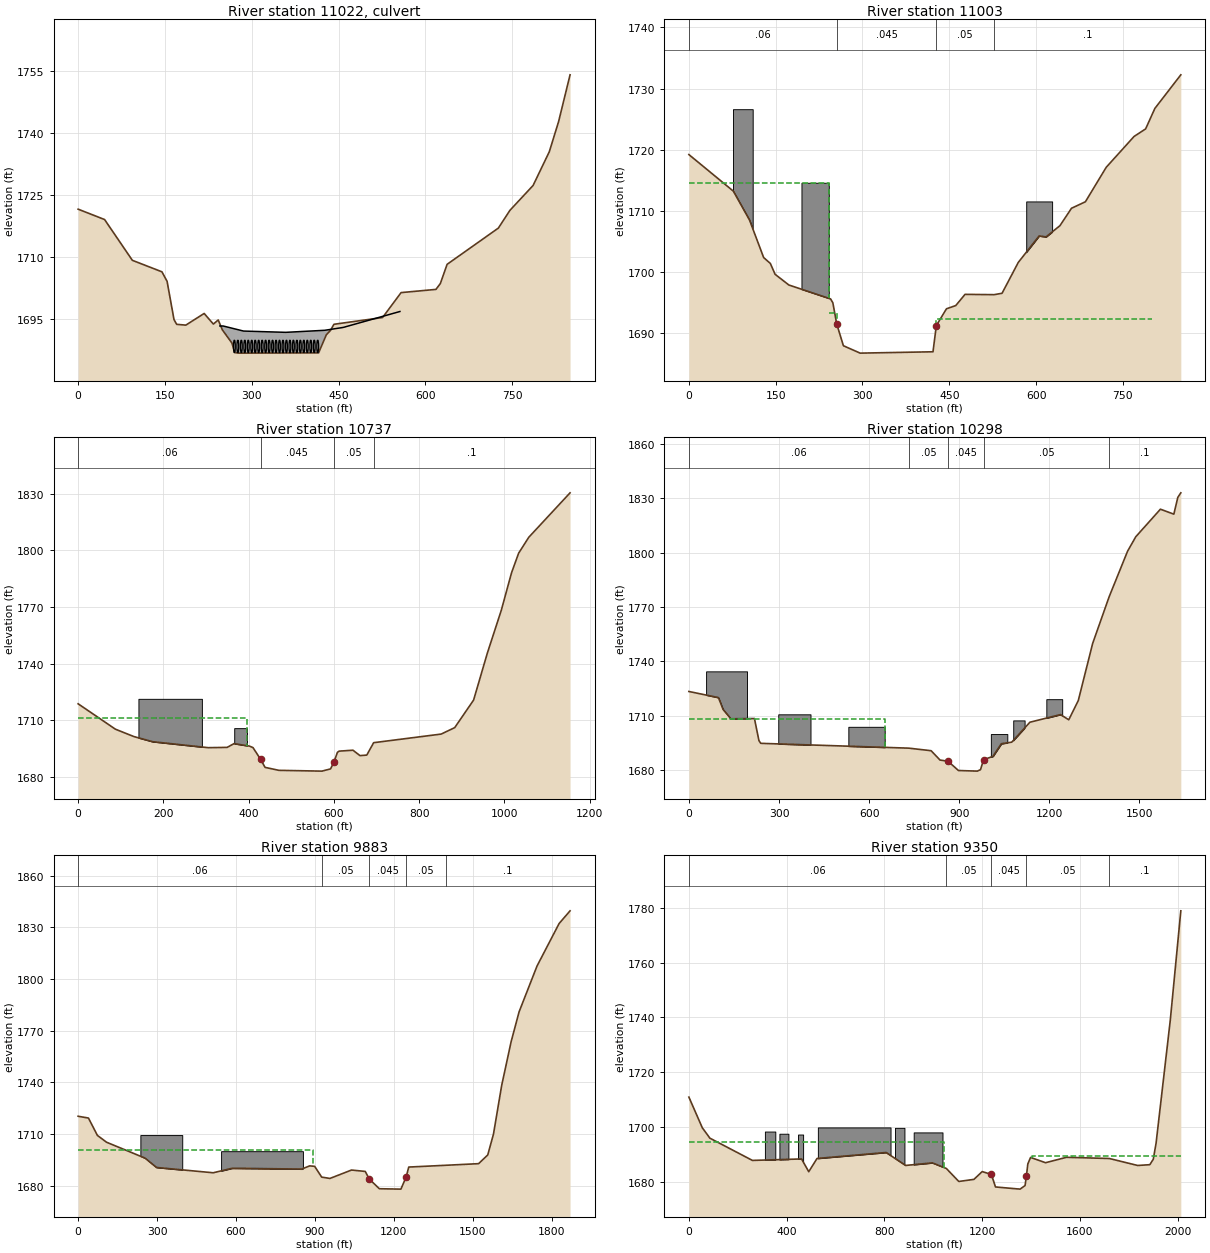
Type RM Length L Ch R = 2 ,11022   ,,,
BEGIN DESCRIPTION:
Dickenson Mountain Road
Incorporated survey data from 54071SPR020RP
END DESCRIPTION:
Bridge Culvert--1,0,-1,-1, 0
Deck Dist Width WeirC Skew NumUp NumDn MinLoCord MaxHiCord MaxSubmerge Is_Ogee
13,25,2.6,0, 7, 7, , , 0.98, 0, 0,0,,
     245  250.64  285.89   358.8  426.19  458.03  556.06
1693.4211693.421  1692.21691.8911692.3851693.071 1696.91
                                                        
     245  250.64  285.89   358.8  426.19  458.03  556.06
1693.4211693.421  1692.21691.8911692.3851693.071 1696.91
                                                        
BR Coef=-1 , 1 , 0 ,, 0 ,,,0.8,0,,0,
WSPro=,,,, 1 ,,,, 0 ,,,, 0 ,,,,-1 ,-1 ,-1 , 0 , 0 , 0 , 0 , 0
Multiple Barrel Culv=1,3,,22,0.024,0.7,1,2,2,1687,1686.9, 25,Culvert #1  , 0 ,15
     270     270     276     276     282     282     288     288     294     294
     300     300     306     306     312     312     318     318     324     324
     330     330     336     336     342     342     348     348     354     354
     360     360     366     366     372     372     378     378     384     384
     390     390     396     396     402     402     408     408     414     414
BC Culvert Barrel=1,Barrel1,0
BC Culvert Barrel=2,Barrel2,0
BC Culvert Barrel=3,Barrel3,0
BC Culvert Barrel=4,Barrel4,0
BC Culvert Barrel=5,Barrel5,0
BC Culvert Barrel=6,Barrel6,0
BC Culvert Barrel=7,Barrel7,0
BC Culvert Barrel=8,Barrel8,0
BC Culvert Barrel=9,Barrel9,0
BC Culvert Barrel=10,Barrel10,0
BC Culvert Barrel=11,Barrel11,0
BC Culvert Barrel=12,Barrel12,0
BC Culvert Barrel=13,Barrel13,0
BC Culvert Barrel=14,Barrel14,0
BC Culvert Barrel=15,Barrel15,0
BC Culvert Barrel=16,Barrel16,0
BC Culvert Barrel=17,Barrel17,0
BC Culvert Barrel=18,Barrel18,0
BC Culvert Barrel=19,Barrel19,0
BC Culvert Barrel=20,Barrel20,0
BC Culvert Barrel=21,Barrel21,0
BC Culvert Barrel=22,Barrel22,0
BC Culvert Barrel=23,Barrel23,0
BC Culvert Barrel=24,Barrel24,0
BC Culvert Barrel=25,Barrel25,0
Culvert Bottom n=0.024
BC Design=,, 0 ,, 0 ,,,,,,
BC Use User HTab Curves=0
BC User HTab FreeFlow(D)= 0

Type RM Length L Ch R = 1 ,11003   ,257.9,265.7,295.3
BEGIN DESCRIPTION:
Incorporated survey data from 54071SPR018CD
END DESCRIPTION:
XS GIS Cut Line= 6
2445024.93695964601751.6814008062445021.54326564601501.065760314
2445019.18533072 601392.912761392445014.91696656601325.677003473
2445011.17287955601294.0556756412445018.57411148600902.030869141
#Sta/Elev= 30
       0 1719.21    76.8 1713.23   104.8  1708.5   129.2 1702.37   140.8  1701.4
     149 1699.63   172.8 1697.88   244.8 1695.61   248.8 1694.97   255.4 1691.54
     267 1687.95  295.93 1686.74  421.83 1686.96  427.64 1691.25   445.1 1693.99
   461.2 1694.52   477.2 1696.35   527.5  1696.3   541.2 1696.53   569.2 1701.57
   605.2  1705.9   617.2 1705.75   641.2 1707.58   661.2 1710.43   685.2 1711.49
   721.2 1717.13   769.3 1722.17   789.3 1723.41   805.3 1726.76   850.1 1732.25
#Mann= 4 ,-1 , 0
       0     .06       0   255.4    .045       0  427.64     .05       0
   527.5      .1       0
#XS Ineff= 3 ,-1
       0   241.8  1714.6   241.8   255.4 1693.36  427.64     800 1692.39
Permanent Ineff=
       F       F       F
#Block Obstruct= 3 ,-1
   76.22  110.26 1726.63  194.53   241.81714.602  582.93  627.711711.547
Bank Sta=255.4,427.64
XS Rating Curve= 0 ,0
Exp/Cntr=0.5,0.3

Type RM Length L Ch R = 1 ,10737   ,400.4,438.5,459.8
XS GIS Cut Line= 2
2445204.80241355601968.6438933912445376.24334364600827.150769562
#Sta/Elev= 30
       0  1718.8    87.6 1705.36   131.2 1701.45   174.7 1698.76   305.1 1695.61
   349.6 1695.75   365.8 1697.75   402.2 1696.42   410.3 1695.63   428.1 1689.47
   438.6 1685.19     471 1683.62   572.1  1683.2   592.3 1684.38   600.4 1688.07
   608.5 1693.17   612.5 1693.77   644.9 1694.26   661.4  1691.4   677.3 1691.69
   693.4 1698.24   851.8 1702.79   883.6  1706.2   927.9 1720.76   960.4 1745.75
   992.8 1768.18    1017 1788.11  1033.6 1798.45  1057.5 1806.89  1154.3 1830.38
#Mann= 4 ,-1 , 0
       0     .06       0   428.1    .045       0   600.4     .05       0
   693.4      .1       0
#XS Ineff= 2 , 0
          396.83 1711.56
Permanent Ineff=
       F       F
#Block Obstruct= 2 ,-1
  141.47  290.371721.439  366.22  396.231705.933
Bank Sta=428.1,600.4
XS Rating Curve= 0 ,0
Exp/Cntr=0.3,0.1

Type RM Length L Ch R = 1 ,10298   ,399.7,415,420.3
XS GIS Cut Line= 3
 2445351.2145223602412.0757493082445906.76984164601070.929809555
 2445993.5754423600905.999365151
#Sta/Elev= 30
       0 1723.33    98.5 1719.94   113.8 1713.43   139.8 1708.24   218.3  1708.4
   233.2 1696.23   239.2 1694.69   732.2 1692.03   806.6 1690.61   836.3 1685.45
   862.9  1684.8   897.6 1679.68   960.4 1679.34   971.1 1680.16   981.11685.621
  1012.6 1687.53  1040.4 1694.47    1075 1695.34  1135.6 1706.36  1237.4 1710.57
  1264.9 1707.69  1296.6 1718.33  1344.5 1749.89  1399.6 1775.75  1460.7  1800.8
  1487.9 1808.76  1570.1 1824.01  1614.8 1821.27    1628 1830.54    1638 1833.05
#Mann= 5 ,-1 , 0
       0     .06       0   732.2     .05       0   862.9    .045       0
   981.1     .05       0  1399.6      .1       0
#XS Ineff= 2 , 0
          653.25 1707.94
Permanent Ineff=
       F       F
#Block Obstruct= 6 ,-1
    57.3  193.571734.443  297.57  404.951710.715  530.94  652.041703.819
 1005.46  1060.3 1699.81 1079.95 1117.851707.356  1190.2 1243.021719.079
Bank Sta=862.9,981.1
XS Rating Curve= 0 ,0
Exp/Cntr=0.3,0.1

Type RM Length L Ch R = 1 ,9883    ,442.9,533.9,551.6
XS GIS Cut Line= 4
2445520.48518114602707.2145947222445646.35336772602529.263178974
2445776.56176873602333.9505774832446410.24225989601066.589595139
#Sta/Elev= 30
       0  1720.4    39.2 1719.36    73.2 1709.29   108.2 1705.31   254.5 1696.11
   297.7 1690.69   513.3 1687.61   585.8 1690.23   849.7 1689.75     880 1691.61
   898.9 1691.34   925.7 1685.09     957 1684.32    1039 1689.19  1091.2 1688.39
  1106.6 1683.97  1144.8 1678.35  1226.8 1678.12  1246.7 1685.15  1256.6 1690.92
  1396.7 1691.95    1522 1692.89  1556.8 1697.94  1578.6 1710.03  1609.9 1738.38
  1645.7 1763.66    1676 1780.99  1744.1 1807.55  1828.1 1832.22  1869.7 1839.58
#Mann= 5 ,-1 , 0
       0     .06       0   925.7     .05       0  1106.6    .045       0
  1246.7     .05       0  1396.7      .1       0
#XS Ineff= 2 , 0
          892.03 1700.93
Permanent Ineff=
       F       F
#Block Obstruct= 2 ,-1
  236.52  395.681709.474  543.35  854.361700.131
Bank Sta=1106.6,1246.7
XS Rating Curve= 0 ,0
Exp/Cntr=0.3,0.1

Type RM Length L Ch R = 1 ,9350    ,840.9,925.9,977.8
XS GIS Cut Line= 2
2445624.65196756 602850.443638982447065.62415122 601444.19382681
#Sta/Elev= 30
       0 1710.87    54.9 1699.67      86 1695.86     260 1687.73   461.2 1688.27
   490.5  1683.6   524.5 1688.44   807.3 1690.63   887.1 1685.89   996.8 1686.84
  1053.7 1684.79  1104.7 1680.04  1166.6  1680.8  1200.5 1683.65  1238.1 1682.61
  1254.9 1678.03  1355.5 1677.24  1375.9 1678.55  1381.5 1682.05  1387.2 1686.43
  1398.5 1688.82  1459.8 1686.89  1545.5 1688.87    1721 1688.43  1836.9 1685.88
  1886.5 1686.17  1900.8 1688.17  1912.2 1694.08  1970.3 1738.97  2013.4 1778.94
#Mann= 5 ,-1 , 0
       0     .06       0  1053.7     .05       0  1238.1    .045       0
  1381.5     .05       0    1721      .1       0
#XS Ineff= 2 , 0
         1045.79 1694.52 1403.34         1689.25
Permanent Ineff=
       F       F
#Block Obstruct= 6 ,-1
   311.1  353.711698.286   370.5  407.321697.492  446.73  467.521697.195
  527.84  825.311699.792  843.52  882.181699.631  920.04 1037.951697.967
Bank Sta=1238.1,1381.5
XS Rating Curve= 0 ,0
Exp/Cntr=0.3,0.1