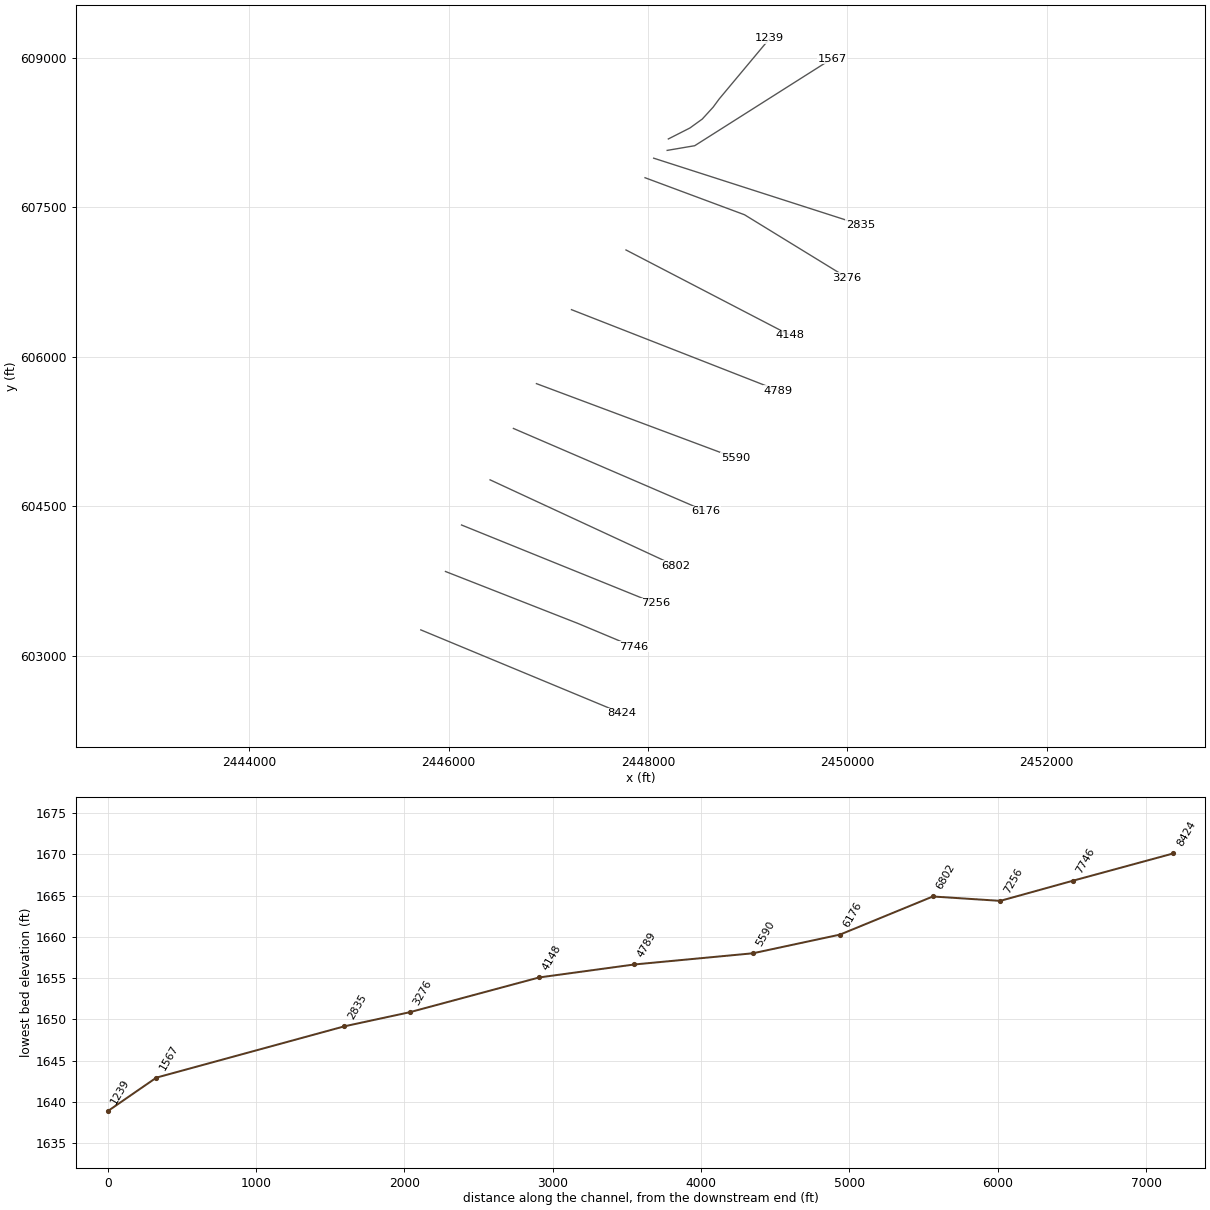
HEC-RAS study SBPOTOMC1.prj: SBPOTOMC1

--- SBPOTOMC1.g01 (geometry) --- (continued)

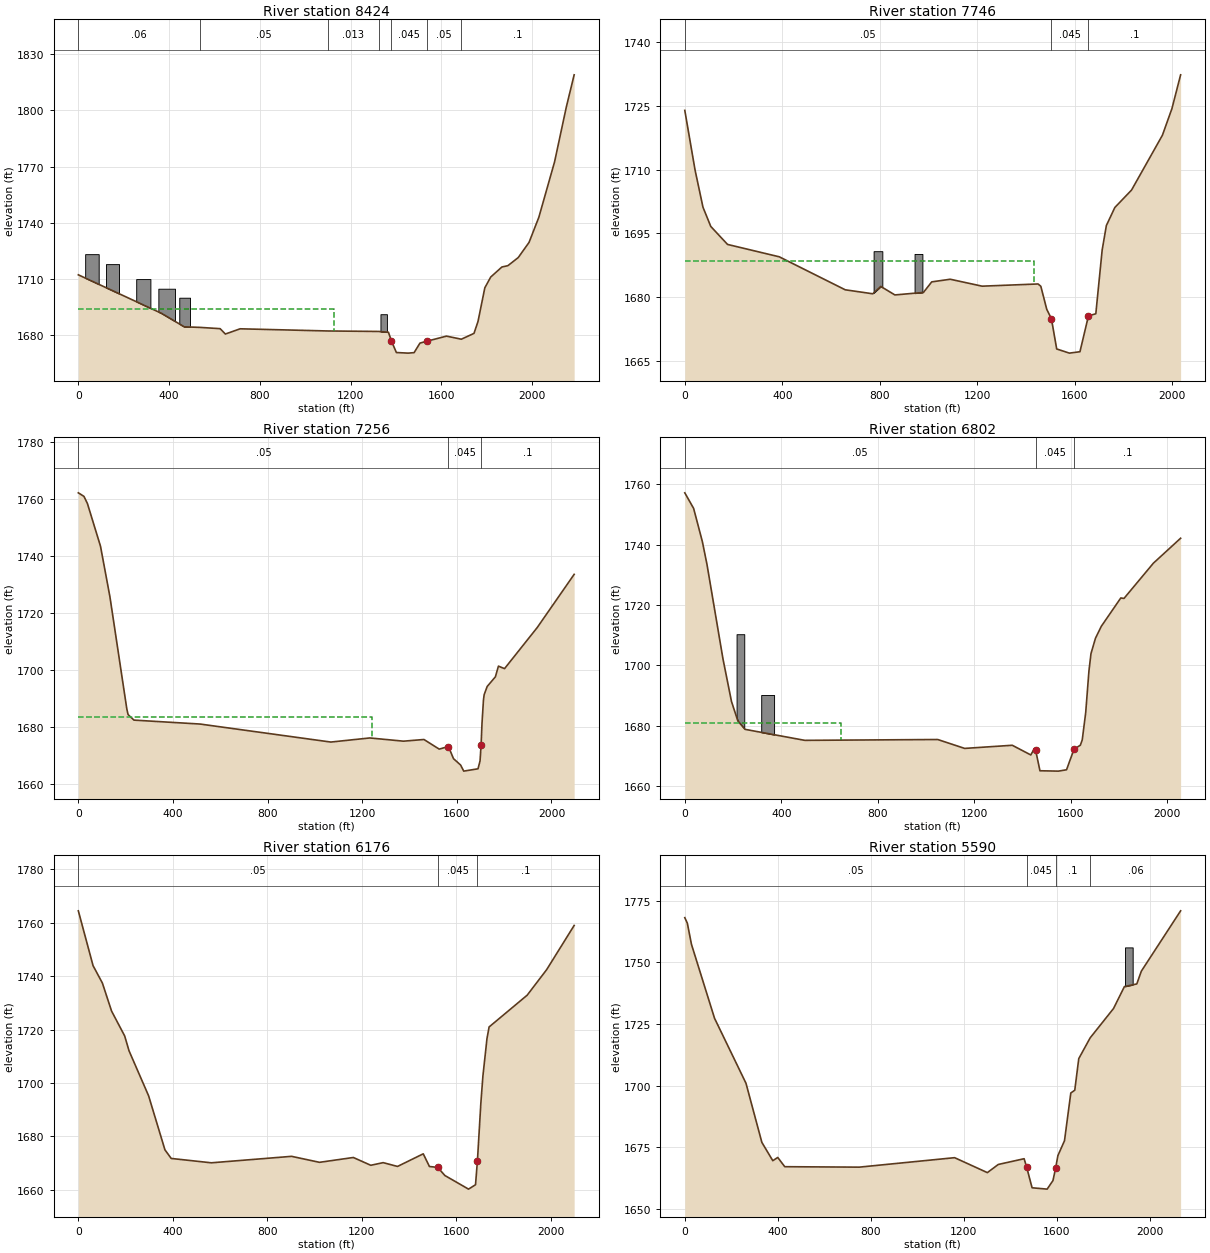
Type RM Length L Ch R = 1 ,8424    ,699.1,677.6,666.1
XS GIS Cut Line= 2
2445720.13799706603258.429699644 2447738.3672283602420.756178141
#Sta/Elev= 30
       0 1712.03   366.6 1691.41   466.8  1684.2   537.2 1683.89   624.9 1683.21
   648.1 1680.34   713.1 1683.14  1098.5 1681.98  1323.8 1681.72  1366.7  1681.3
    1380 1676.63  1401.7 1670.44  1453.7 1670.12  1479.9 1670.39  1505.6 1675.48
  1535.9 1676.49  1622.6 1679.22    1688 1677.57  1743.8 1680.69  1761.5  1687.1
  1791.5 1705.07  1817.5 1710.85  1866.6  1716.2  1893.1 1716.93  1938.7 1721.25
  1986.4 1729.38  2029.7 1742.88    2099 1772.54  2150.9 1801.96  2185.2 1819.07
#Mann= 7 ,-1 , 0
       0     .06       0   537.2     .05       0  1098.5    .013       0
  1323.8     .05       0    1380    .045       0  1535.9     .05       0
    1688      .1       0
#XS Ineff= 2 , 0
         1127.76 1693.97
Permanent Ineff=
       F       F
#Block Obstruct= 6 ,-1
   30.09   89.751723.095  121.75  179.331717.761  255.07  317.661709.748
  352.67  425.931704.601  444.81  492.231699.776  1331.5 1360.011690.951
Bank Sta=1380,1535.9
XS Rating Curve= 0 ,0
Exp/Cntr=0.3,0.1

Type RM Length L Ch R = 1 ,7746    ,493.5,489.7,484.4
XS GIS Cut Line= 3
2445967.53382772603844.3671760562447295.65879613603323.533900142
2447855.55465797603089.159040809
#Sta/Elev= 30
       0 1723.92    42.1 1709.88    74.6 1701.13   106.6 1696.61   175.3 1692.38
   387.5 1689.47   657.9 1681.71     771 1680.77   803.9  1682.5   861.6  1680.5
   978.8 1681.09  1012.8 1683.57  1088.7 1684.19  1219.4 1682.56    1449 1683.08
  1460.3 1682.53  1484.5 1677.12  1503.7  1674.9  1525.3 1667.79  1577.4 1666.81
  1620.7 1667.14  1655.6 1675.57  1685.8 1676.07  1711.8 1691.07    1729 1696.82
  1763.8 1701.07  1832.3 1705.17    1959 1718.08    1998 1724.34  2033.6 1732.28
#Mann= 3 ,-1 , 0
       0     .05       0  1503.7    .045       0  1655.6      .1       0
#XS Ineff= 2 , 0
          1431.6 1688.44
Permanent Ineff=
       F       F
#Block Obstruct= 2 ,-1
  774.43  810.19 1690.79  942.35  974.451690.141
Bank Sta=1503.7,1655.6
XS Rating Curve= 0 ,0
Exp/Cntr=0.3,0.1

Type RM Length L Ch R = 1 ,7256    ,483.9,454.6,458.3
XS GIS Cut Line= 2
2446128.70279673  604310.80259492448071.41118164603524.344194055
#Sta/Elev= 30
       0 1762.02    23.8 1760.77    38.4 1758.27    93.7 1743.29   133.6 1725.52
     205 1686.17   210.4  1684.2   235.2 1682.27   514.5 1680.89  1067.4 1674.57
  1232.1 1676.01  1374.6 1674.88  1460.8 1675.47  1525.5 1672.09  1564.4 1673.01
  1585.9 1668.74  1616.1 1666.49  1629.1 1664.37  1689.5 1665.19  1698.1 1667.97
  1702.4 1673.42  1706.3 1681.06  1712.5 1689.28  1715.4 1691.17  1728.3 1694.08
  1762.9 1697.45  1775.8 1701.21  1801.6 1700.33  1939.8 1714.75  2095.9 1733.41
#Mann= 3 ,-1 , 0
       0     .05       0  1564.4    .045       0  1702.4      .1       0
#XS Ineff= 2 , 0
         1240.81 1683.22
Permanent Ineff=
       F       F
Bank Sta=1564.4,1702.4
XS Rating Curve= 0 ,0
Exp/Cntr=0.3,0.1

Type RM Length L Ch R = 1 ,6802    ,628.8,626.1,617.4
XS GIS Cut Line= 2
2446415.16121331604763.9273448142448279.74442638603899.344100222
#Sta/Elev= 30
       0 1757.15    36.6 1751.99    72.8 1740.99    92.1 1733.36   158.3 1702.08
   193.5    1688     220 1681.52   249.7 1678.75   497.5  1675.1  1048.4 1675.38
  1160.2 1672.43  1357.5 1673.47  1434.3 1670.26  1449.4 1672.43  1454.5 1671.74
  1472.2 1665.02  1548.8  1664.9  1582.4 1665.35  1613.3 1672.15  1639.7  1673.5
  1647.5 1675.25  1661.8 1684.27  1675.3 1698.13  1683.8 1703.88  1702.4 1708.96
  1726.5  1712.9  1807.3  1722.3  1820.5 1722.14  1942.3 1733.82  2055.3  1742.1
#Mann= 3 ,-1 , 0
       0     .05       0  1454.5    .045       0  1613.3      .1       0
#XS Ineff= 2 , 0
          645.85 1680.85
Permanent Ineff=
       F       F
#Block Obstruct= 2 ,-1
  214.55  246.481710.287  316.71  370.111690.134
Bank Sta=1454.5,1613.3
XS Rating Curve= 0 ,0
Exp/Cntr=0.3,0.1

Type RM Length L Ch R = 1 ,6176    ,557,586.1,587.7
XS GIS Cut Line= 2
2446649.53607264605279.552625895 2448577.4875973604448.823316231
#Sta/Elev= 30
       0 1764.43    62.3 1743.93   101.9 1737.39   140.7 1726.92   196.2 1717.61
   214.7 1712.04   297.5 1695.22   366.7 1674.99   393.3 1671.76   563.2 1670.13
   902.9 1672.55  1021.1 1670.31  1164.3 1672.12  1238.3  1669.2  1290.6 1670.19
  1351.5 1668.77  1460.4 1673.49  1486.6 1668.74  1521.4 1668.43  1551.9 1665.38
  1652.1 1660.28  1681.7 1661.92  1689.8 1670.93  1704.3 1692.48    1713 1702.63
  1730.2 1716.62  1739.2 1720.97  1900.3 1732.85    1983 1742.43  2099.3 1758.96
#Mann= 3 ,-1 , 0
       0     .05       0  1521.4    .045       0  1689.8      .1       0
Bank Sta=1521.4,1689.8
XS Rating Curve= 0 ,0
Exp/Cntr=0.3,0.1

Type RM Length L Ch R = 1 ,5590    ,803.9,800.9,818.5
XS GIS Cut Line= 2
2446880.43882605605729.2052698882448876.96665713604982.677563474
#Sta/Elev= 30
       0 1768.18      11 1765.93    28.5 1757.42   127.9 1727.35     263 1700.99
   331.3 1676.99   378.3 1669.56   399.6 1670.87   429.7 1667.12   749.8 1666.94
  1159.9 1670.78  1300.7 1664.72  1347.7 1668.03  1458.7 1670.36 1469.36 1667.02
  1492.9 1658.57  1557.7 1658.02  1582.7 1661.49  1594.1 1666.52  1603.9 1671.62
  1632.3 1677.66  1659.4 1697.03  1676.5 1698.17  1693.6 1710.98  1742.6  1719.4
    1843 1731.31    1890 1740.23  1943.1 1741.29  1962.6 1746.47  2131.5 1770.96
#Mann= 4 ,-1 , 0
       0     .05       0 1469.36    .045       0  1594.1      .1       0
  1742.6     .06       0
#Block Obstruct= 1 ,-1
 1892.43 1925.351756.118
Bank Sta=1469.36,1594.1
XS Rating Curve= 0 ,0
Exp/Cntr=0.3,0.1

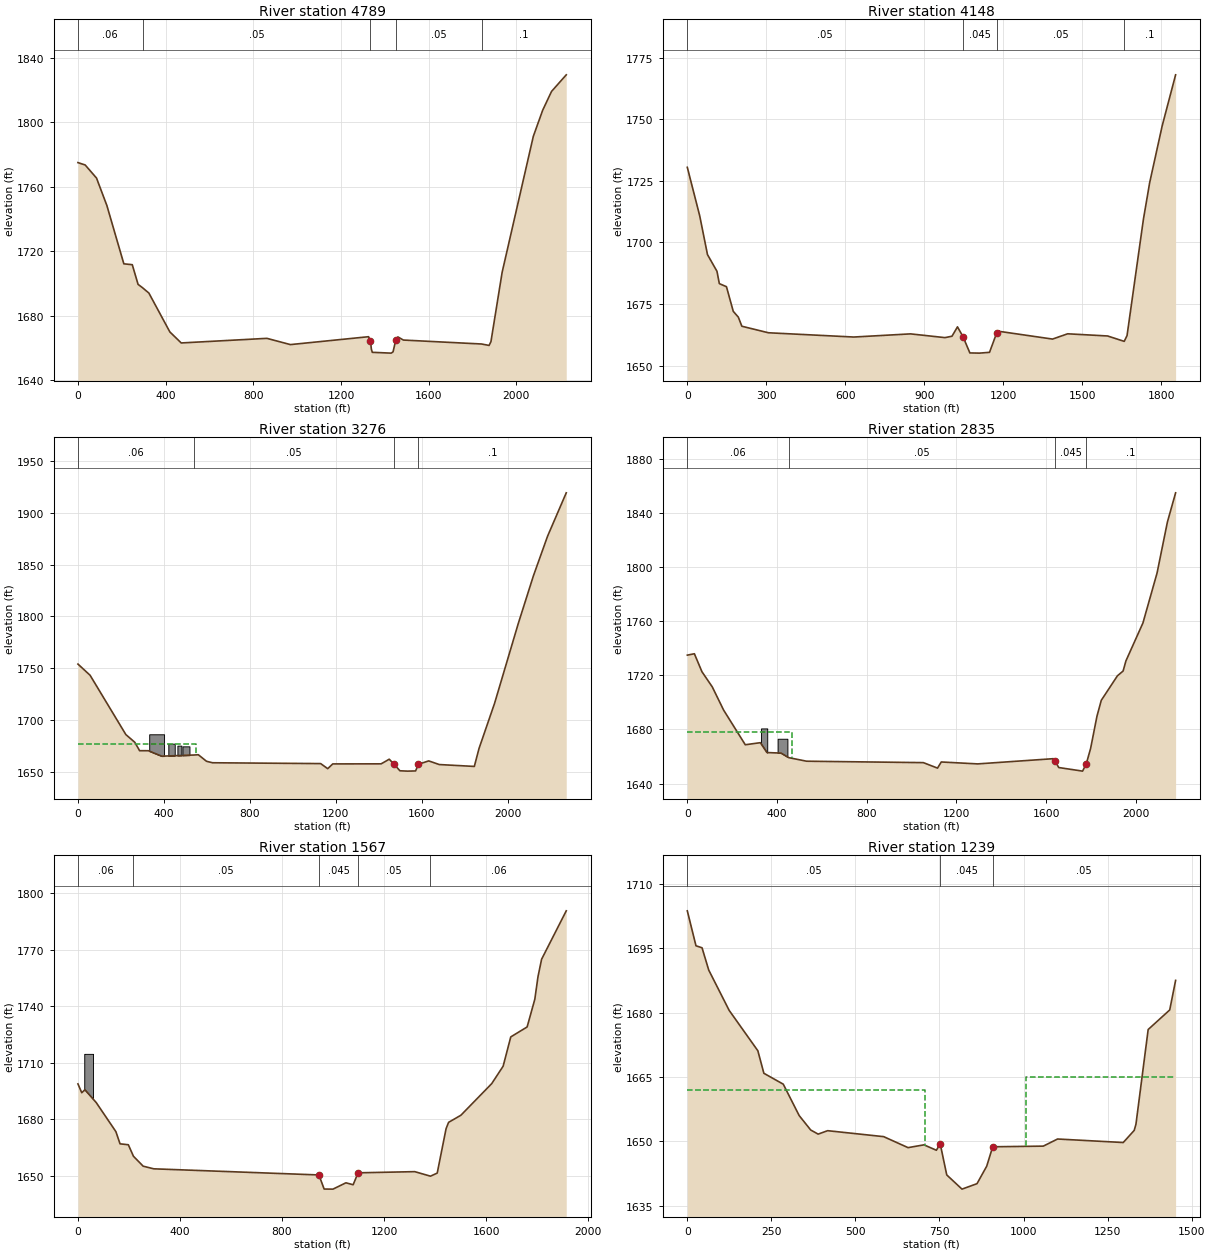
Type RM Length L Ch R = 1 ,4789    ,674.7,640.7,600.3
XS GIS Cut Line= 2
2447232.00144313606471.3927619012449306.65411797605659.760854974
#Sta/Elev= 30
       0 1774.99      33 1773.51    84.6 1765.42   131.8 1748.39   209.4 1712.12
   247.8 1711.59   274.2 1699.38     295 1697.23   323.6 1693.97   419.3 1669.83
   471.1 1662.98     862 1665.84   969.4 1661.96  1325.9 1666.86  1334.5  1664.2
  1338.8 1659.02    1343 1657.16  1428.9 1656.66  1437.5 1657.42  1450.4 1664.99
  1459.7 1666.71  1484.8 1664.78  1841.3 1662.33  1875.7 1661.44  1884.2 1663.78
  1935.2 1706.81  2077.5  1791.3  2120.4 1807.57  2160.6 1819.19  2227.8 1829.51
#Mann= 5 ,-1 , 0
       0     .06       0     295     .05       0  1334.5    .045       0
  1450.4     .05       0  1841.3      .1       0
Bank Sta=1334.5,1450.4
XS Rating Curve= 0 ,0
Exp/Cntr=0.3,0.1

Type RM Length L Ch R = 1 ,4148    ,922.8,872,813.7
XS GIS Cut Line= 2
2447778.87633364607070.3512096412449423.84154764606215.316502392
#Sta/Elev= 30
       0 1730.48      47 1710.85    76.6 1695.07   112.6  1688.3   121.6 1683.29
   148.6 1682.05   174.5 1672.04   193.7  1669.7   207.1    1666     308 1663.35
     632 1661.62   847.4  1662.9   978.1 1661.38  1004.9 1661.95  1025.8 1665.75
  1046.6 1661.79  1072.8 1655.17    1109 1655.09  1147.4 1655.41  1174.1 1663.12
  1180.1 1663.99  1386.5 1660.79  1444.1 1662.93  1595.7 1662.05  1658.8 1659.86
  1669.5 1662.19  1731.8 1709.49  1755.5  1724.3    1803 1747.34  1853.9 1768.01
#Mann= 4 ,-1 , 0
       0     .05       0  1046.6    .045       0  1174.1     .05       0
  1658.8      .1       0
Bank Sta=1046.6,1174.1
XS Rating Curve= 0 ,0
Exp/Cntr=0.3,0.1

Type RM Length L Ch R = 1 ,3276    ,308.8,440.8,434.7
XS GIS Cut Line= 3
2447969.84872071607795.1775158942448968.11247222607423.649715647
 2449996.7583808606792.573221892
#Sta/Elev= 30
       0  1754.1    56.4 1743.33   222.9 1686.12   264.6 1678.66   286.9 1670.57
   327.5 1670.56   389.7 1665.31   538.1  1666.4   560.1 1666.69   598.1 1660.37
   626.1 1658.95  1129.3 1658.14  1162.1 1653.25  1185.6 1657.84  1410.8 1657.91
  1448.4 1662.37  1471.5 1657.42  1498.1 1651.21  1533.2 1650.88  1570.8 1651.06
  1584.5 1657.48  1631.9 1660.75  1681.3 1657.22  1844.2 1655.41    1866 1672.62
  1938.6 1716.35    2049 1793.38  2119.4 1839.32  2185.1 1877.42    2272 1919.22
#Mann= 4 ,-1 , 0
       0     .06       0   538.1     .05       0  1471.5    .045       0
  1584.5      .1       0
#XS Ineff= 2 , 0
          548.33 1676.76
Permanent Ineff=
       F       F
#Block Obstruct= 4 ,-1
  331.51  400.651686.403  420.44  450.281677.407   462.7  481.341675.479
  486.26  518.821674.781
Bank Sta=1471.5,1584.5
XS Rating Curve= 0 ,0
Exp/Cntr=0.3,0.1

Type RM Length L Ch R = 1 ,2835    ,870.2,1267.7,1309.6
XS GIS Cut Line= 2
2448056.65432139607991.3578978032450129.57077922607324.691252142
#Sta/Elev= 30
       0  1734.9    31.6 1735.92    65.2 1722.66   111.4 1711.41   161.9  1694.3
   258.5 1668.67   325.7 1670.19   355.1  1662.9   418.2 1662.49   451.8 1659.16
   531.6  1656.5  1052.6 1655.45  1115.7  1651.4  1132.5 1655.93  1294.9 1654.51
  1632.5 1658.37  1640.9 1656.47  1656.2 1651.83  1762.7 1649.17  1779.5 1654.76
  1798.3 1665.84  1826.9 1689.82    1846 1701.49  1918.2 1719.66  1943.4 1723.16
    1956 1730.67  2031.7 1758.62  2094.7 1795.53  2140.9 1833.26  2177.5 1854.86
#Mann= 4 ,-1 , 0
       0     .06       0   451.8     .05       0  1640.9    .045       0
  1779.5      .1       0
#XS Ineff= 2 , 0
          467.78 1678.02
Permanent Ineff=
       F       F
#Block Obstruct= 2 ,-1
  328.71  356.461680.733  402.87  446.321673.101
Bank Sta=1640.9,1779.5
XS Rating Curve= 0 ,0
Exp/Cntr=0.3,0.1

Type RM Length L Ch R = 1 ,1567    ,287.6,328.4,383.8
XS GIS Cut Line= 3
2448192.07071722608069.4830696432448468.11248797  608116.3579759
2449848.32068555608991.358194396
#Sta/Elev= 30
       0 1698.76    14.9 1694.07    27.1 1695.67    71.7 1688.85   148.8 1673.43
     165 1666.97   197.5 1666.49   217.7 1660.36   255.7 1655.12   297.3 1653.72
   944.6 1650.47   965.1 1642.99   999.7 1642.95  1050.4  1646.3  1078.8 1645.28
  1098.2  1651.6  1320.3 1652.22  1381.9 1649.82  1408.4 1651.46  1443.1 1675.02
  1452.9 1678.37  1501.1 1682.13    1622 1698.91  1666.8 1708.17  1696.7 1723.69
  1760.8 1728.97    1791 1743.69  1803.4 1755.64  1817.6  1764.9  1914.2 1790.57
#Mann= 5 ,-1 , 0
       0     .06       0   217.7     .05       0   944.6    .045       0
  1098.2     .05       0  1381.9     .06       0
#Block Obstruct= 1 ,-1
   24.68   59.16  1714.7
Bank Sta=944.6,1098.2
XS Rating Curve= 0 ,0
Exp/Cntr=0.5,0.3

Type RM Length L Ch R = 1 ,1239    ,175.8,174.5,178
BEGIN DESCRIPTION:
Incorporated survery from 54071SPR012BU
END DESCRIPTION:
XS GIS Cut Line= 6
2448203.73902499608184.203888256 2448420.5537981608294.372964319
2448544.13530242608383.7318982122448653.31881048608503.254511803
2448714.08246847 608585.719898062449221.89510113609193.792828888
#Sta/Elev= 30
       0 1703.74    25.8 1695.59    43.8 1695.13    63.7 1689.94   124.5 1680.54
   209.8 1671.13   227.7 1665.88   285.4 1663.34   332.8 1656.01     367 1652.66
   389.1  1651.7   417.4  1652.5   584.1 1651.11   656.5 1648.55   703.9  1649.2
   740.8 1647.94  752.17 1649.44  771.61 1642.19  816.97 1638.88  861.62 1640.15
  890.51 1644.23   908.3 1648.75  1058.7  1648.9  1101.3 1650.56  1296.5 1649.74
  1329.2 1652.57  1334.4 1654.03  1370.7 1676.08  1434.8 1680.64  1452.3 1687.53
#Mann= 3 ,-1 , 0
       0     .05       0  752.17    .045       0   908.3     .05       0
#XS Ineff= 2 ,-1
       0   708.4 1662.03  1008.4  1451.9 1664.91
Permanent Ineff=
       F       F
Bank Sta=752.17,908.3
XS Rating Curve= 0 ,0
Exp/Cntr=0.5,0.3