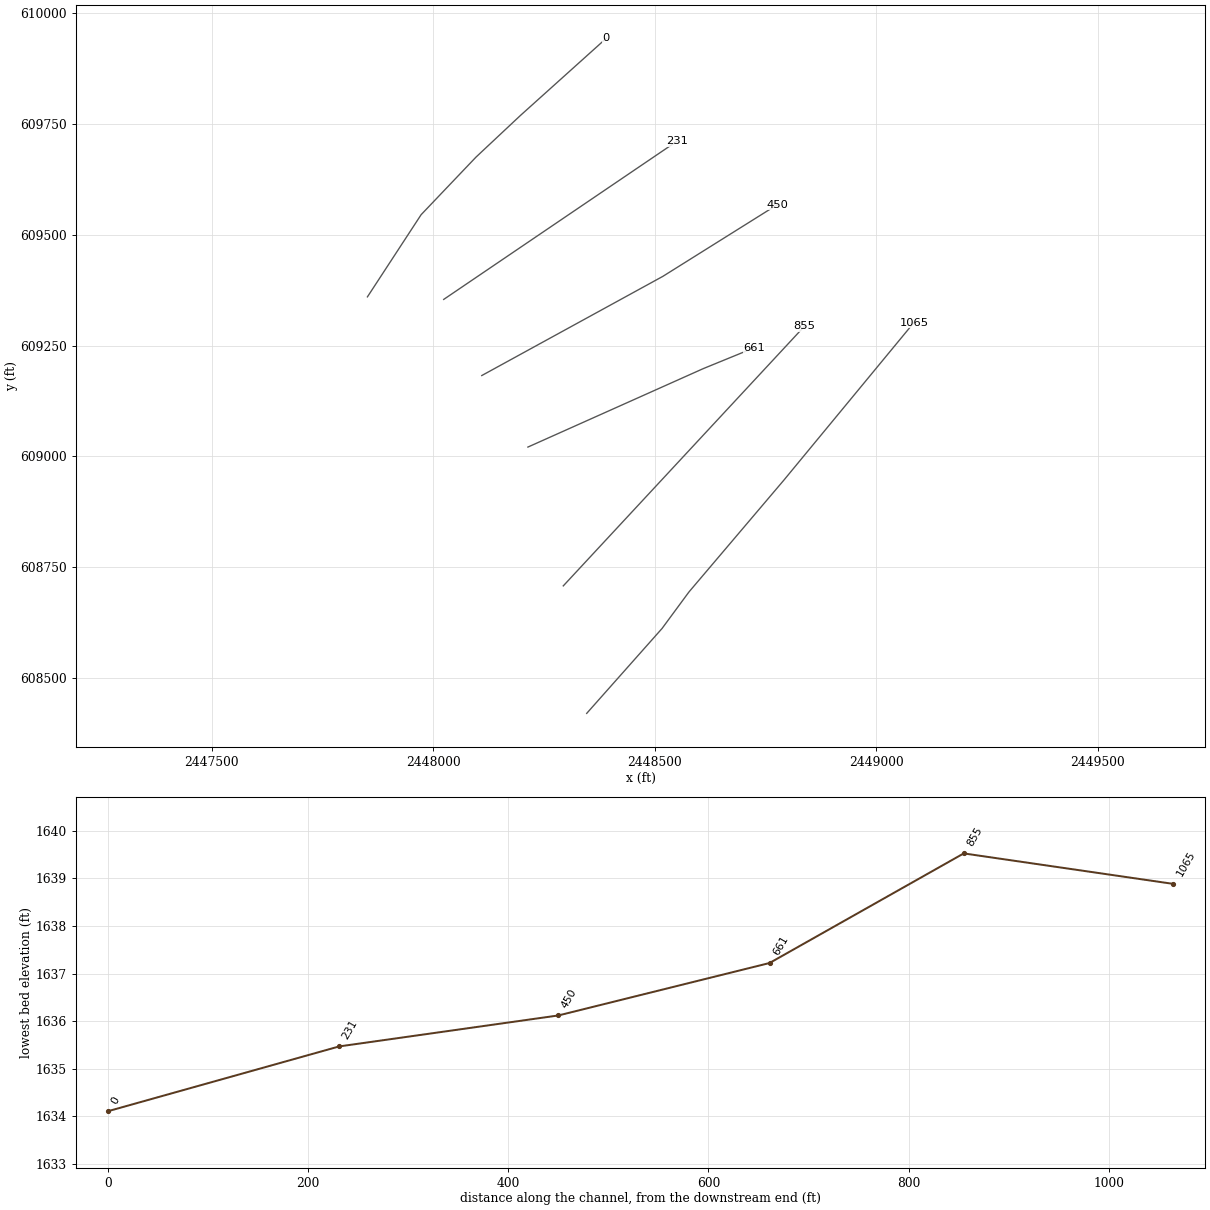
HEC-RAS study SBPOTOMC1.prj: SBPOTOMC1

--- SBPOTOMC1.g01 (geometry) --- (continued)

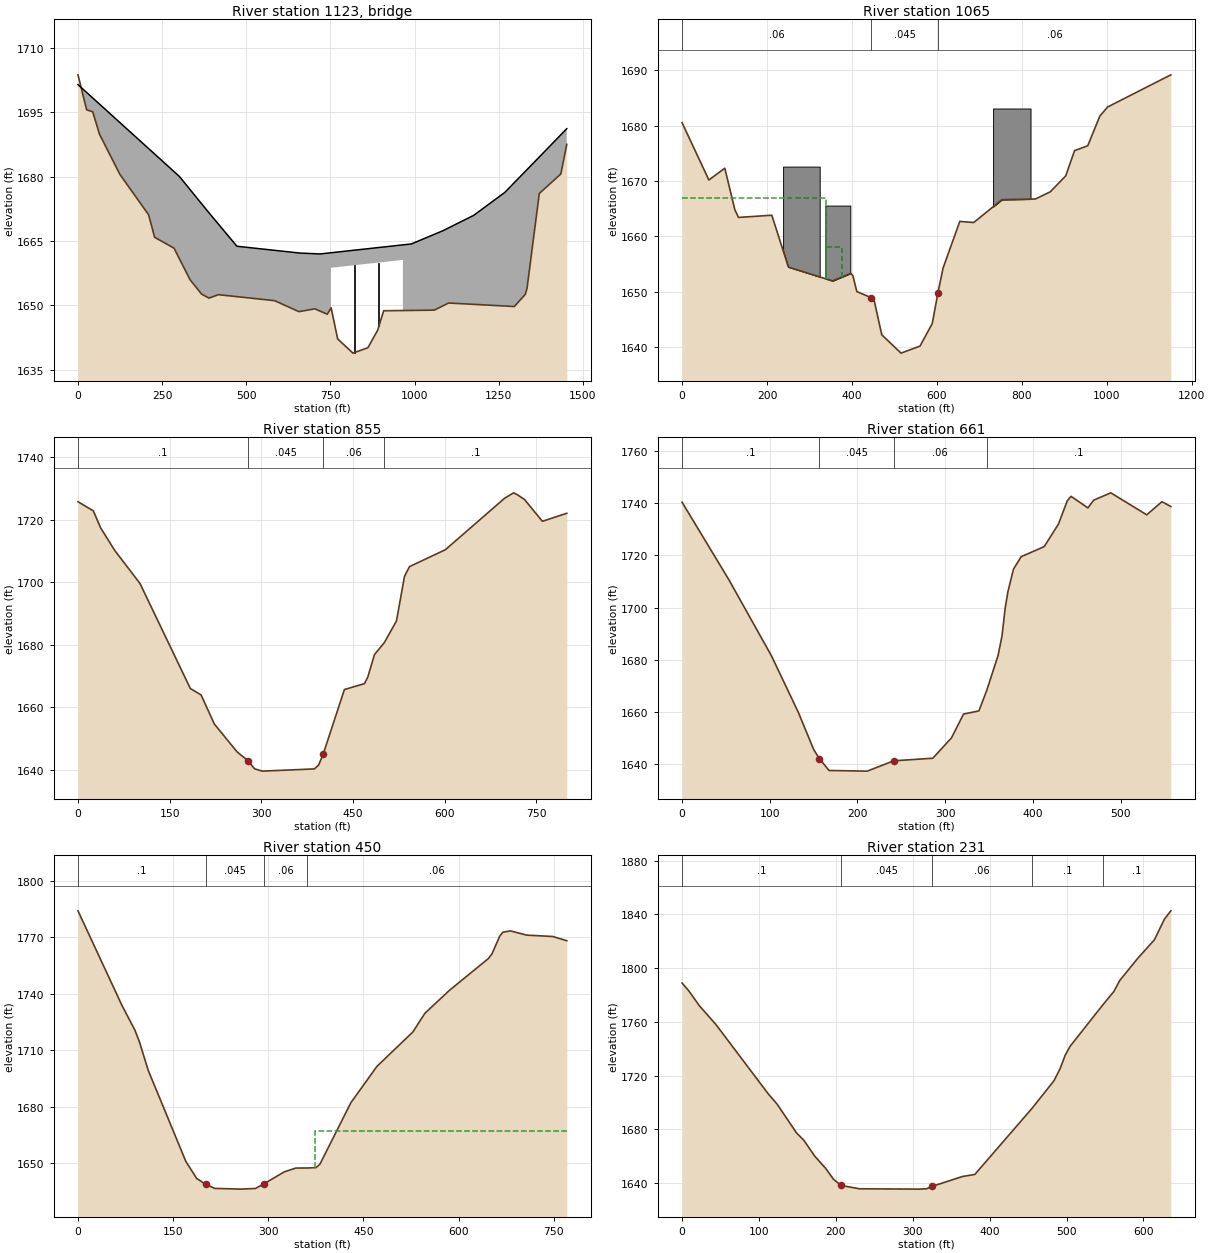
Type RM Length L Ch R = 3 ,1123    ,,,
BEGIN DESCRIPTION:
Blue Gray Trail
Incorporate survey data from 54071SPR010RP
END DESCRIPTION:
Bridge Culvert--1,0,-1,-1, 0
Deck Dist Width WeirC Skew NumUp NumDn MinLoCord MaxHiCord MaxSubmerge Is_Ogee
43,34,2.6,0, 16, 14, , , 0.98, 0, 0,0,,
       0   301.4  386.82  472.24  659.44  719.36   751.4   751.4   965.4   965.4
  990.73 1083.61 1175.79 1267.97 1360.16 1452.34
 1701.46 1680.05 1671.81 1663.791662.1981661.994 1662.27 1662.27 1664.11 1664.11
1664.329 1667.38 1670.99 1676.32 1683.74 1691.19
                                                         1658.77 1660.61
                                                
       0   85.42  170.84  358.04     410     410     624     624  689.33  782.21
  874.39  966.57 1058.76 1150.94
 1680.05 1671.81 1663.791662.198 1662.47 1662.47 1663.59 1663.591664.329 1667.38
 1670.99 1676.32 1683.74 1691.19
                                         1658.97 1660.09
                                
Pier Skew, UpSta & Num, DnSta & Num=  ,821, 2 ,480, 2 , 0 , 0 , 0 ,,
       3       3
       0    1661
       3       3
       0    1661
Pier Skew, UpSta & Num, DnSta & Num=  ,894, 2 ,553, 2 , 0 , 0 , 0 ,,
       3       3
       0    1661
       3       3
       0    1661
BR Coef=-1 , 1 , 0 ,0.9, 0 ,,,0.8,0,1.2,0,
WSPro=,,,, 1 ,,,, 0 ,,,, 0 ,,,,-1 ,-1 ,-1 , 0 , 0 , 0 , 0 , 0
BR U #Sta/Elev= 30
       0 1703.74    25.8 1695.59    43.8 1695.13    63.7 1689.94   124.5 1680.54
   209.8 1671.13   227.7 1665.88   285.4 1663.34   332.8 1656.01     367 1652.66
   389.1  1651.7   417.4  1652.5   584.1 1651.11   656.5 1648.55   703.9  1649.2
   740.8 1647.94  752.17 1649.44  771.61 1642.19  816.97 1638.88  861.62 1640.15
  890.51 1644.23   908.3 1648.75  1058.7  1648.9  1101.3 1650.56  1296.5 1649.74
  1329.2 1652.57  1334.4 1654.03  1370.7 1676.08  1434.8 1680.64  1452.3 1687.53
BR U #Mann= 3
       0     .05  752.17     .04   908.3     .05
BR D #Sta/Elev= 30
       0 1680.53    63.1 1670.18   100.6 1672.31   124.3 1664.79   132.9 1663.41
   211.3 1663.81   250.3 1654.44   354.3 1651.93   396.9  1653.3   402.1 1652.91
   411.5    1650   445.6  1648.9  452.96 1648.17  470.21 1642.19  515.57 1638.88
  560.22 1640.15  589.11 1644.23  602.37 1649.75  614.52 1654.25   653.9 1662.69
   686.8 1662.49   752.9 1666.62   831.7 1666.74     867 1668.04   903.3 1670.92
   924.1 1675.48   955.2 1676.37   983.7 1681.74  1001.9 1683.37  1150.9 1689.19
BR D #Mann= 3
       0     .06   445.6     .04  602.37     .06
BC Design=,, 0 ,, 0 ,,,,,,
BC Use User HTab Curves=0
BC User HTab FreeFlow(D)= 0

Type RM Length L Ch R = 1 ,1065    ,214.8,209.5,207.7
BEGIN DESCRIPTION:
Incorporated survery from 54071SPR008BD for overbanks and 54071SPR012BU for channel
END DESCRIPTION:
XS GIS Cut Line= 5
2448346.50446346608419.660846978 2448516.5999238608611.327458397
2448577.36358181608693.7928446382448791.77325797608946.396998227
2449085.17621447609301.865775481
#Sta/Elev= 30
       0 1680.53    63.1 1670.18   100.6 1672.31   124.3 1664.79   132.9 1663.41
   211.3 1663.81   250.3 1654.44   354.3 1651.93   396.9  1653.3   402.1 1652.91
   411.5    1650   445.6  1648.9  452.96 1648.17  470.21 1642.19  515.57 1638.88
  560.22 1640.15  589.11 1644.23  602.37 1649.75  614.52 1654.25   653.9 1662.69
   686.8 1662.49   752.9 1666.62   831.7 1666.74     867 1668.04   903.3 1670.92
   924.1 1675.48   955.2 1676.37   983.7 1681.74  1001.9 1683.37  1150.9 1689.19
#Mann= 3 ,-1 , 0
       0     .06       0   445.6    .045       0  602.37     .06       0
#XS Ineff= 3 ,-1
       0     338    1667     338 376.667    1658 657.333    1000 1660.09
Permanent Ineff=
       F       F       F
#Block Obstruct= 3 ,-1
  237.89  324.011672.602  337.39  396.081665.553  732.34  820.451683.104
Bank Sta=445.6,602.37
XS Rating Curve= 0 ,0
Exp/Cntr=0.5,0.3

Type RM Length L Ch R = 1 ,855     ,218.1,194,163.3
XS GIS Cut Line= 2
2448293.63350622608707.5037752242448837.90407123 609293.44125165
#Sta/Elev= 30
       0  1725.8    25.1 1722.88    37.1 1717.41    60.4 1710.12   101.5 1699.61
   183.8 1665.99   201.5  1663.9     223 1654.64   260.2 1645.71   277.7 1642.91
     289 1640.27   301.4 1639.52   386.8 1640.23   393.8 1641.49   401.3 1645.02
   435.9 1665.65   468.7 1667.54   474.1 1669.61   485.1 1676.86   501.2 1680.67
   521.1 1687.62   534.2  1701.9   542.4 1705.02   601.1 1710.43     698 1726.91
   712.8 1728.65   718.7 1728.06   730.7 1726.49   759.8 1719.53   799.7  1722.1
#Mann= 4 ,-1 , 0
       0      .1       0   277.7    .045       0   401.3     .06       0
   501.2      .1       0
Bank Sta=277.7,401.3
XS Rating Curve= 0 ,0
Exp/Cntr=0.3,0.1

Type RM Length L Ch R = 1 ,661     ,205.2,210.9,218.5
XS GIS Cut Line= 3
2448213.77211739609020.871914893 2448609.6056433609197.955222145
2448724.18907556609244.830128387
#Sta/Elev= 30
       0 1740.42    53.7 1710.49   101.9 1681.49   132.5 1659.84   150.1  1645.5
   156.7 1641.95   167.6 1637.47   211.2 1637.22   241.4 1641.18   285.9 1642.17
   307.2 1649.97     321 1659.12   338.5 1660.33   347.4 1668.17   360.4 1681.65
   364.8 1689.05   368.6 1700.11   371.6 1706.09   377.9 1714.72   386.7 1719.52
     413 1723.39   429.2 1732.04   439.2  1740.9   443.5 1742.68   462.8 1738.25
   469.4 1741.22   488.9 1744.03   529.9 1735.59   547.2 1740.63   557.4 1738.77
#Mann= 4 ,-1 , 0
       0      .1       0   156.7    .045       0   241.4     .06       0
   347.4      .1       0
Bank Sta=156.7,241.4
XS Rating Curve= 0 ,0
Exp/Cntr=0.3,0.1

Type RM Length L Ch R = 1 ,450     ,211.6,219,227.8
XS GIS Cut Line= 3
2448109.60565905609182.3302533922448518.45982823609406.288466901
2448776.27230471  609567.7468054
#Sta/Elev= 30
       0 1783.94    69.7 1733.43    89.7 1720.59    97.1 1714.08   110.8 1699.13
     170 1650.86   186.9 1641.86     201 1638.74   215.7  1636.5   256.7 1636.12
   279.5 1636.46   292.6 1638.83   325.1 1645.29   343.4 1647.31   361.6 1647.34
   375.3 1647.56   381.4 1649.41     430 1681.95   471.2 1701.33   527.8 1719.57
   546.7 1729.49   585.8  1741.8   646.8 1758.57   652.6 1761.13   664.7 1770.47
   669.5 1772.56   681.6 1773.28   707.2 1771.04   748.3 1770.31   770.4 1768.07
#Mann= 4 ,-1 , 0
       0      .1       0     201    .045       0   292.6     .06       0
   361.6     .06       0
#XS Ineff= 2 , 0
                          373.81          1667.2
Permanent Ineff=
       F       F
Bank Sta=201,292.6
XS Rating Curve= 0 ,0
Exp/Cntr=0.3,0.1

Type RM Length L Ch R = 1 ,231     ,216.6,231.1,244.1
XS GIS Cut Line= 2
2448023.66816689609354.2052377312448549.70976572609710.976177722
#Sta/Elev= 30
       0 1788.86     8.6 1783.17    22.6 1771.91      44 1758.02   112.1 1706.35
   123.7 1698.67   148.7 1677.42   158.4 1671.78   172.6 1659.95   186.5 1651.07
     197 1642.76   206.7  1638.2   230.9 1635.71   308.2 1635.47   317.9 1635.74
   325.3 1637.55   364.7 1644.88   380.7 1646.41   454.9 1695.48   483.7  1716.2
   491.9 1725.59   498.1 1735.04   504.6 1741.81     547 1772.53   561.4 1782.53
   569.2 1790.82   593.1 1807.65   614.1 1820.96   627.2 1836.41   635.6 1842.62
#Mann= 5 ,-1 , 0
       0      .1       0   206.7    .045       0   325.3     .06       0
   454.9      .1       0     547      .1       0
Bank Sta=206.7,325.3
XS Rating Curve= 0 ,0
Exp/Cntr=0.3,0.1

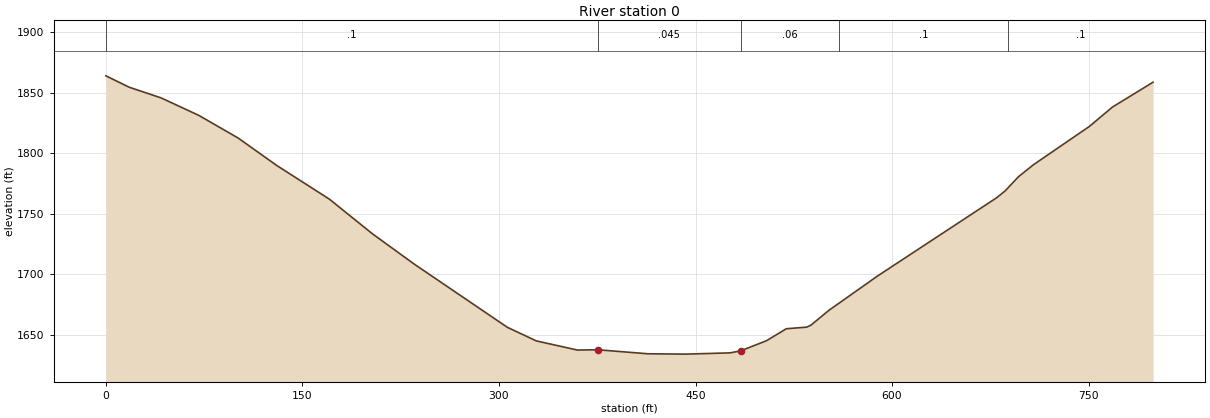
Type RM Length L Ch R = 1 ,0       ,1.92,1.92,1.92
XS GIS Cut Line= 6
2447851.46903622 609359.960147472447972.65317705609545.445668891
 2448096.5633623609675.4755925542448111.99935505609689.944723725
2448196.85023522609769.4796696452448390.61461148609943.622037888
#Sta/Elev= 30
       0 1864.09    17.8 1854.67    42.1 1845.86      71 1831.36   101.1 1812.57
   130.3 1790.07   170.7 1762.08   203.4 1733.56   235.4 1708.45   306.4 1656.27
   328.5 1645.04   359.9 1637.47   375.41637.721   413.6  1634.4   442.5 1634.11
   476.4 1635.15   484.4 1636.81   504.2  1645.2   519.3 1655.09   534.8  1656.4
   538.1 1658.06   551.9 1670.38   589.1 1698.79   679.8 1763.31   686.4 1769.07
   696.3 1780.53   707.9  1790.6   750.6 1822.27   768.1 1838.19   799.2 1858.82
#Mann= 5 ,-1 , 0
       0      .1       0   375.4    .045       0   484.4     .06       0
  559.88      .1       0  688.24      .1       0
Bank Sta=375.4,484.4
XS Rating Curve= 0 ,0
Exp/Cntr=0.3,0.1
LCMann Table=0

Chan Stop Cuts=-1
Use User Specified Reach Order=0
Composite Channel Slope=5